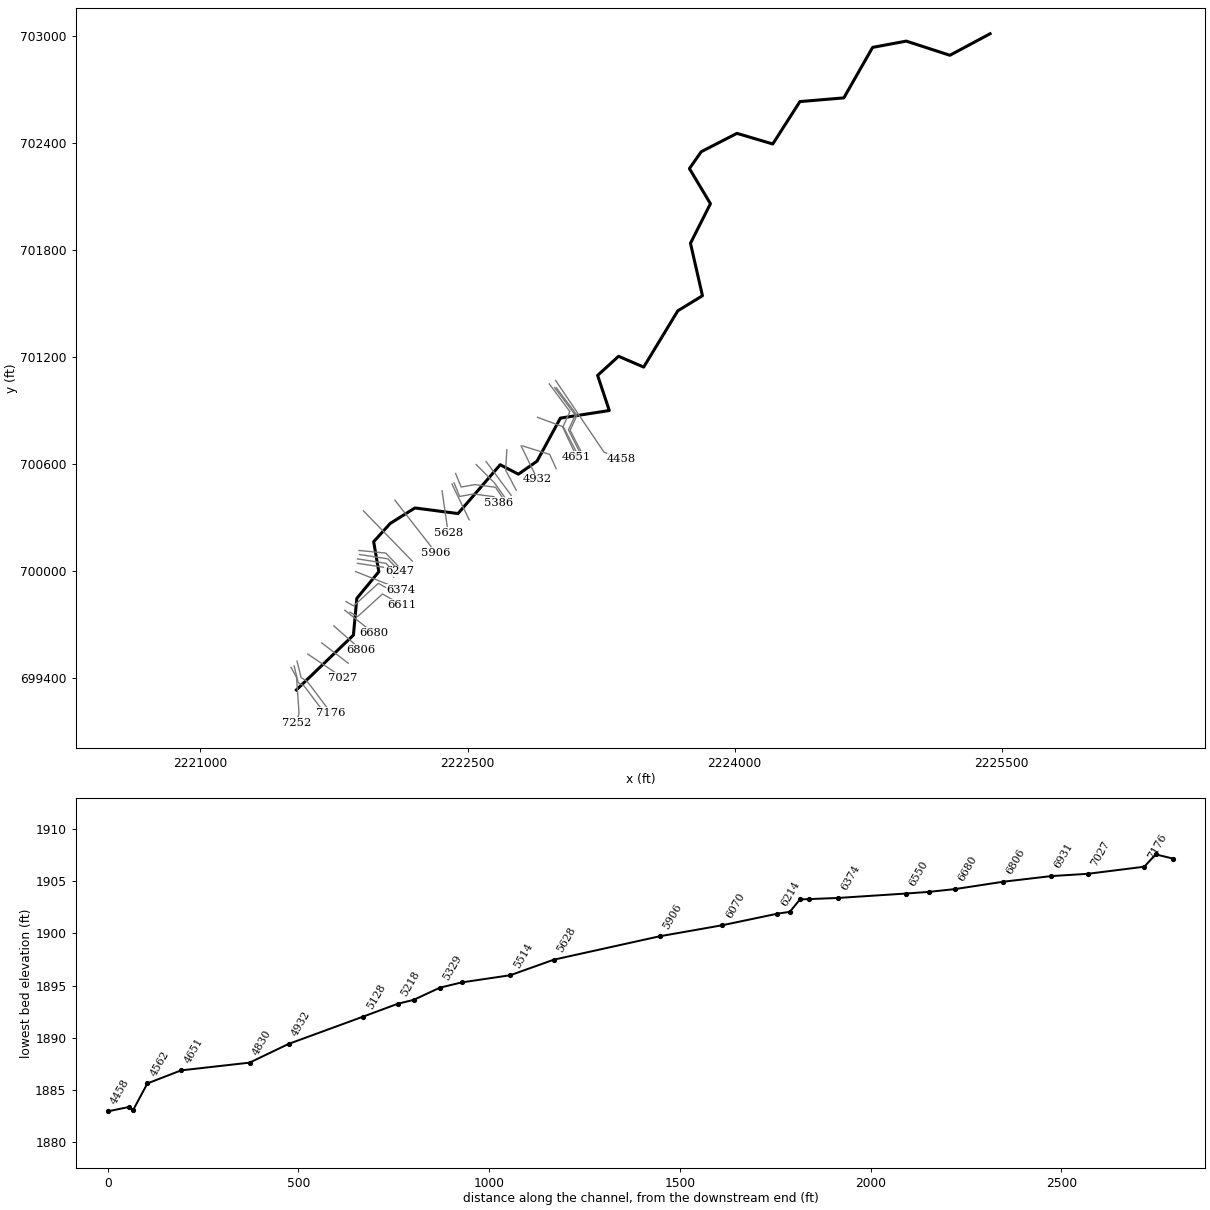
--- GUMRN.prj (project) ---

Proj Title=GUMRN
Current Plan=p01
Default Exp/Contr=0,0
English Units
Geom File=g01
Flow File=f01
Plan File=p01
BEGIN DESCRIPTION:
---------- MODELED AS PART OF WVEMD CTP PROGRAM, 2023----------
Stream Name: Gum Run
Flood Zone:  AFH
Upshur County, WV
HEC-RAS Version: RAS 6.3
Vertical Datum: NAVD88
Projection: NAD 1983 StatePlane West Virginia S FIPS 4702 (US Feet)
Terrain: 1-meter LIDAR (FEMA Region III 3DEP collected 2016-2018)
Land Use: 2019 NLCD
Hydrologic Method:
WV 2010 Regional Regression Equations
Additional Model Notes:
None
END DESCRIPTION:
DSS Export Rating Curves= 0
DSS Export Rating Curve Sorted= 0
DSS Export Volume Flow Curves= 0
DXF OffsetX= 0
DXF OffsetY= 0
DXF ScaleX= 0
DXF ScaleY= 0

--- GUMRN.p01 (plan) ---

Plan Title=Floodplain
Program Version=4.00
Geom File=g01
Flow File=f01
K Sum by GR=0
Std Step Tol=0.01
Critical Tol=0.01
Num of Std Step Trials=20
Max Error Tol=0.3
Flow Tol Ratio=0.001
Split Flow NTrial=30
Split Flow Tol=0.02
Split Flow Ratio=0.02
Log Output Level=0
Friction Slope Method=1
Unsteady Friction Slope Method=2
Unsteady Bridges Friction Slope Method=1
Global Log Level=0
CheckData=False
Run HTab=0
Run UNet=0
Run PostProcess=0
UNET Theta=0
UNET Theta Warmup=0
UNET ZTol=0
UNET ZSATol=0
UNET MxIter=0
UNET MaxInSteps=0
UNET DtIC=0
UNET DtMin=0
UNET MaxCRTS=0
UNET WFStab=0
UNET SFStab=0
UNET WFX=0
UNET SFX=0
UNET DSS MLevel=0
UNET DZMax Abort=0
UNET Convert EG Bridges=0
UNET Use Existing IB Tables=0
UNET Froude Limit=0
UNET Froude Power=0
Write IC File=0
Echo Input=False
Echo Output=False
Write Detailed=0

--- GUMRN.f01 (steady flow) ---

Flow Title=Flows
Program Version=4.00
Number of Profiles= 1
Profile Names=01pct
River Rch & RM=GUMRN,Main,7252
     383
River Rch & RM=GUMRN,Main,4651
     429
River Rch & RM=GUMRN,Main,2377
     582
Boundary for River Rch & Prof#=GUMRN,Main      ,1
Up Type=0
Dn Type=3
Dn Slope=0.006398

--- GUMRN.g01 (geometry) ---

Geom Title=Geometry
Program Version=6.31

River Reach=GUMRN           ,Main
Reach XY= 30
2221538.67501974699330.276415248     2221859.079      699638.055
     2221878.081      699844.179     2222001.675      699994.072
      2221972.83      700162.851     2222066.348      700265.784
      2222204.68      700352.234     2222446.545      700320.728
     2222683.403      700595.044     2222785.392      700541.904
     2222890.071      700614.761     2223021.449      700856.798
     2223296.023      700899.408     2223230.491      701096.661
     2223348.334      701204.058     2223489.212      701143.306
     2223680.942      701459.402     2223819.245      701543.964
     2223751.996       701838.77     2223864.144      702060.833
     2223746.073      702258.114     2223812.348      702352.863
     2224013.006      702455.968     2224214.122      702396.274
     2224366.562       702634.42     2224613.264      702655.167
     2224774.832      702938.698     2224964.043      702974.011
     2225208.771      702894.428     2225434.554      703015.361

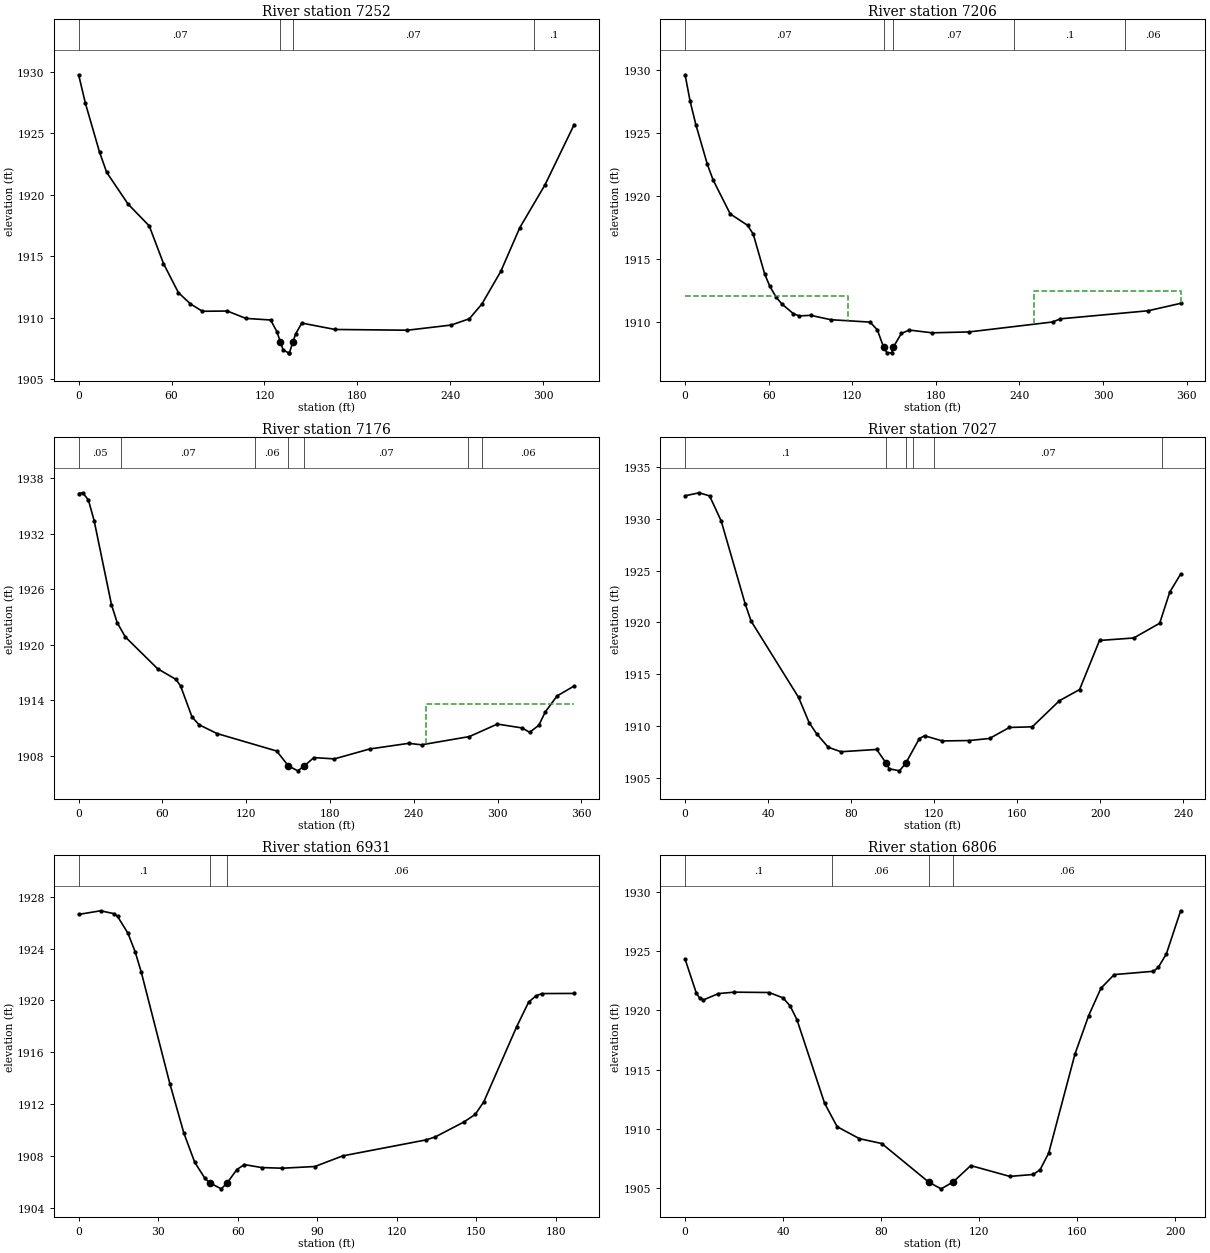
Type RM Length L Ch R = 1 ,7252    ,37.9,46.7,37.9
XS GIS Cut Line= 4
2221508.57451154699457.0085869892221539.58253684699401.385922495
2221553.53664327699201.6978478252221541.50724118699146.843774301
#Sta/Elev= 30
       0 1929.76     4.4 1927.43    13.5 1923.47    18.1 1921.83    31.9 1919.25
    45.6 1917.47    54.8 1914.41    64.4 1912.05    72.2 1911.13    79.9 1910.53
      96 1910.55     108 1909.95     124 1909.82     128 1908.88  130.291908.037
   132.1 1907.37   135.6 1907.15   136.1 1907.15   138.41908.035   140.1 1908.68
   144.1 1909.57   165.6 1909.05   212.3 1908.99   240.6 1909.41   252.3 1909.92
   260.4 1911.12   272.6 1913.77   284.9 1917.33   301.2 1920.82     320 1925.71
#Mann= 4 ,-1,0
       0     .07       0  130.29    .045       0   138.4     .07       0
  293.86      .1       0
Bank Sta=130.29,138.4
XS Rating Curve= 0 ,0
Exp/Cntr(USF)=0,0
Exp/Cntr=0.3,0.1

Type RM Length L Ch R = 1 ,7206    ,29.9,29.6,29.5
XS GIS Cut Line= 5
2221526.14037082699464.6774661632221549.20358989699370.793206665
2221580.01233205699354.0388851422221601.32122867699327.455046931
2221715.54910361699175.803617397
#Sta/Elev= 30
       0 1929.64     3.6 1927.54     7.7 1925.69      16 1922.52    20.1 1921.29
    32.4 1918.59    44.8 1917.69    48.9 1916.99    57.1 1913.83    60.8 1912.85
    65.4 1911.97    69.5 1911.44    77.7 1910.67    81.9 1910.49    90.1 1910.54
   104.6 1910.19   132.8    1910     138 1909.38  142.48 1908.01   144.8 1907.58
   148.2 1907.56   149.5 1908.01   155.2  1909.1   160.9 1909.37   177.2 1909.15
   203.8 1909.22   263.8 1910.01   269.4 1910.26   332.3  1910.9   355.7 1911.49
#Mann= 5 ,-1,0
       0     .07       0  142.48    .045       0   149.5     .07       0
  235.82      .1       0  315.82     .06       0
#XS Ineff= 2 , 0
          117.05 1912.08  250.39         1912.44
Permanent Ineff=
       F       F
Bank Sta=142.48,149.5
XS Rating Curve= 0 ,0
Exp/Cntr(USF)=0,0
Exp/Cntr=0.3,0.1

Type RM Length L Ch R = 1 ,7176    ,143.7,148.6,150.5
XS GIS Cut Line= 5
2221542.42873376699491.9551251772221565.81198484699398.468801999
2221596.88352048 699380.876229592221625.44915529699344.242187871
2221731.31946179699203.360283757
#Sta/Elev= 30
       0 1936.32     2.9  1936.4       7 1935.62    11.1 1933.39    23.5 1924.33
    27.6 1922.38    33.4 1920.84    56.5 1917.41    69.7 1916.25      73 1915.54
    81.2 1912.19    86.2 1911.36      99 1910.41   141.8 1908.52 150.1911906.913
   156.9 1906.38161.55051906.905   168.4 1907.81   183.1 1907.67   208.4 1908.74
   236.3 1909.35   245.5 1909.19   279.8 1910.08   299.8 1911.43   317.5 1911.01
   322.9 1910.54   329.5  1911.3   334.1 1912.74   342.6 1914.47   354.8 1915.54
#Mann= 7 ,-1,0
       0     .05       0      30     .07       0  126.37     .06       0
 150.191    .045       0161.5505     .07       0  278.53      .1       0
  288.53     .06       0
#XS Ineff= 2 , 0
                          249.06         1913.62
Permanent Ineff=
       F       F
Bank Sta=150.191,161.5505
XS Rating Curve= 0 ,0
Exp/Cntr(USF)=0,0
Exp/Cntr=0.3,0.1

Type RM Length L Ch R = 1 ,7027    ,96,96.1,95.6
XS GIS Cut Line= 2
2221602.55749269699531.7483384122221800.57234188699398.271662289
#Sta/Elev= 30
       0  1932.2     6.8 1932.49    11.8 1932.19    17.4 1929.77    28.9 1921.82
    31.8 1920.13    54.7 1912.77    59.8 1910.33    63.5 1909.24      69 1907.97
    75.1 1907.54    92.3 1907.76   96.991906.416    98.4  1905.9   103.3  1905.7
  106.28 1906.42   112.9 1908.81   115.4 1909.08     124 1908.58     137 1908.62
   146.7 1908.82   156.3 1909.88   167.3 1909.94   180.4 1912.46   190.1 1913.53
   199.7 1918.26   216.2  1918.5   228.7 1919.92   233.6 1922.94   238.8 1924.65
#Mann= 6 ,-1,0
       0      .1       0   96.99    .045       0  106.28      .1       0
     110     .06       0     120     .07       0     230     .05       0
Bank Sta=96.99,106.28
XS Rating Curve= 0 ,0
Exp/Cntr(USF)=0,0
Exp/Cntr=0.3,0.1

Type RM Length L Ch R = 1 ,6931    ,124.3,125.6,124.8
XS GIS Cut Line= 2
2221681.44002307699594.1190663792221829.79599317699480.447000549
#Sta/Elev= 30
       0 1926.63     8.3 1926.91    13.5 1926.68    14.7 1926.47    18.6 1925.18
    21.3 1923.76    23.6  1922.2    34.4 1913.59    39.7 1909.77    43.8 1907.52
    47.6  1906.3   49.45 1905.94    53.8 1905.48   56.02 1905.94    59.7 1906.97
    62.5 1907.35      69 1907.12    76.8 1907.07    89.1  1907.2    99.6 1908.02
     131 1909.25   134.5 1909.48   145.3 1910.63   149.6 1911.22   152.8 1912.18
   165.2 1917.97   169.7 1919.86   172.5 1920.36   174.8 1920.53   186.9 1920.54
#Mann= 3 ,-1,0
       0      .1       0   49.45    .045       0   56.02     .06       0
Bank Sta=49.45,56.02
XS Rating Curve= 0 ,0
Exp/Cntr(USF)=0,0
Exp/Cntr=0.3,0.1

Type RM Length L Ch R = 1 ,6806    ,124,125.5,124.4
XS GIS Cut Line= 2
2221748.80158118699690.1558385882221900.52238786699556.679763772
#Sta/Elev= 30
       0  1924.3     4.5 1921.49     5.9 1921.01     7.5 1920.87    13.6  1921.4
    20.1 1921.52    34.3 1921.49    39.9 1921.04    42.8 1920.37    45.6 1919.21
    56.9 1912.15      62 1910.18    71.1 1909.17    80.2 1908.76    99.4  1905.5
   104.4 1904.94  109.21  1905.5   116.5  1906.9   132.4 1905.99     142 1906.15
   144.8 1906.56   148.3 1907.96     159  1916.3   164.6 1919.55   169.6 1921.85
     175    1923     191 1923.28     193 1923.61   196.3 1924.76   202.1 1928.38
#Mann= 4 ,-1,0
       0      .1       0      60     .06       0    99.4    .045       0
  109.21     .06       0
Bank Sta=99.4,109.21
XS Rating Curve= 0 ,0
Exp/Cntr(USF)=0,0
Exp/Cntr=0.3,0.1

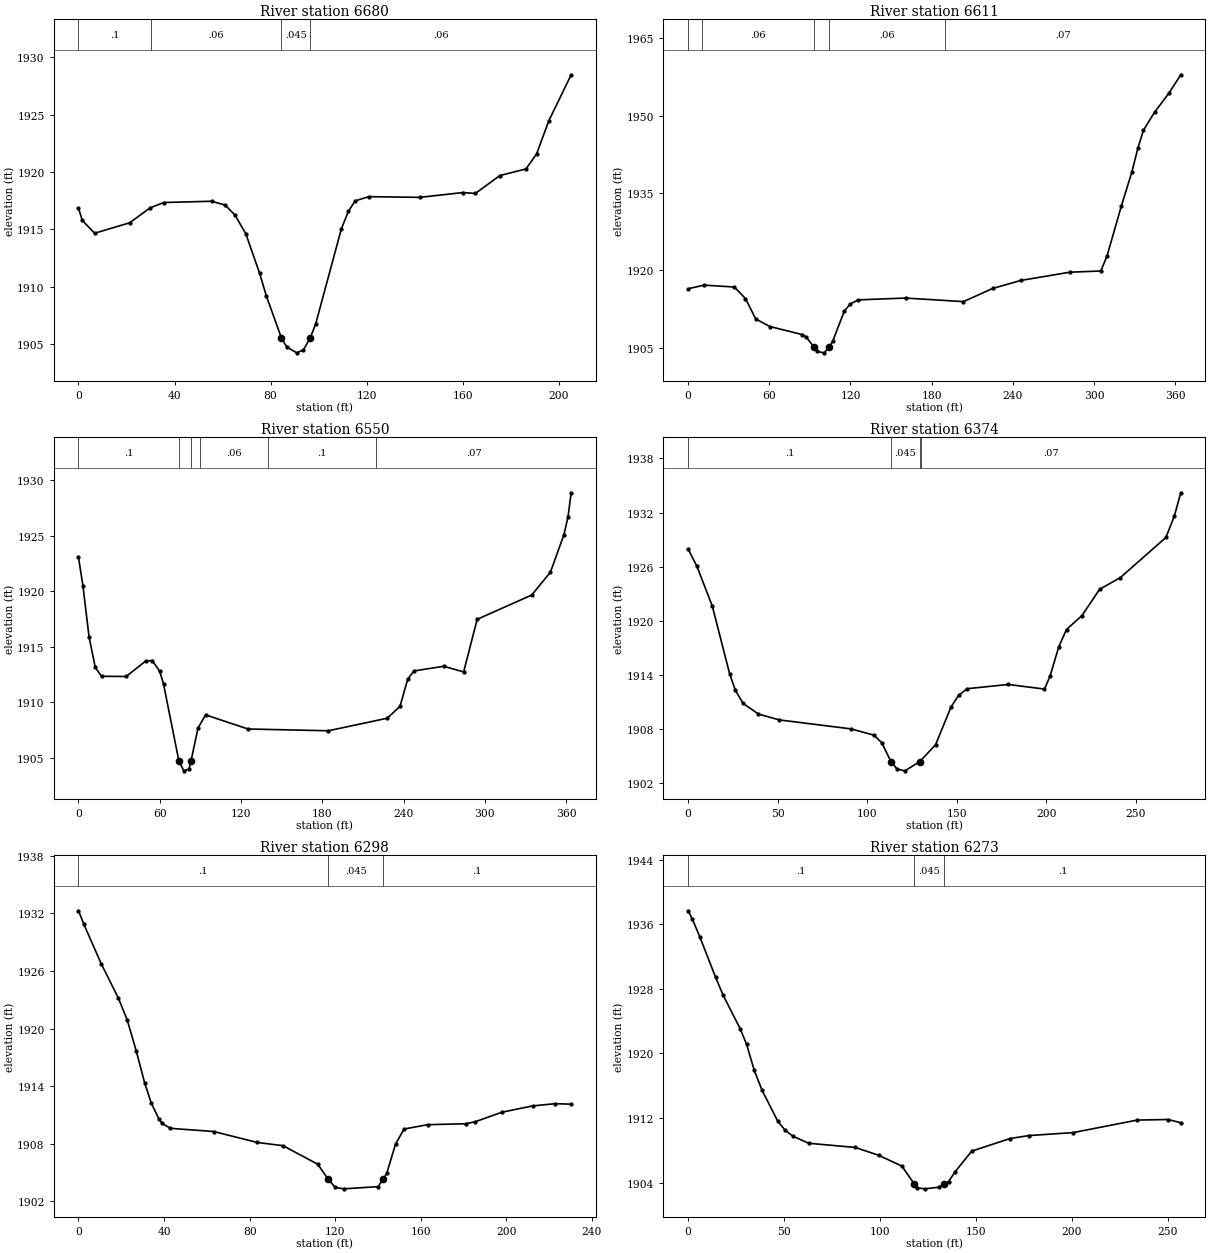
Type RM Length L Ch R = 1 ,6680    ,53.2,69.2,82
XS GIS Cut Line= 2
2221810.89728013699777.7891711462221971.44382753699649.936215714
#Sta/Elev= 30
       0 1916.85     1.6 1915.79     6.7 1914.67    21.3 1915.58    29.8 1916.88
    35.5 1917.35    55.4 1917.46    61.1 1917.13    65.2 1916.25    69.7 1914.62
    75.4  1911.2    78.3 1909.17    84.5 1905.55    86.7 1904.76    90.9 1904.24
    93.7  1904.5   96.54 1905.55    98.8 1906.77   109.5 1915.06   112.4 1916.57
   115.2 1917.49   120.9 1917.86   142.2  1917.8   160.1 1918.22   165.3 1918.14
   175.5  1919.7   186.4 1920.28   190.8 1921.59   195.9 1924.48   205.2 1928.49
#Mann= 4 ,-1,0
       0      .1       0      30     .06       0    84.5    .045       0
   96.54     .06       0
Bank Sta=84.5,96.54
XS Rating Curve= 0 ,0
Exp/Cntr(USF)=0,0
Exp/Cntr=0.3,0.1

Type RM Length L Ch R = 1 ,6611    ,57.5,60.6,54.3
XS GIS Cut Line= 4
2221839.45295871699767.121677494 2221882.7954898699742.152866529
2222021.88777461699869.0099518152222131.81798473699807.747579953
#Sta/Elev= 30
       0 1916.41    11.9 1917.11    34.2 1916.74    42.4 1914.51      50 1910.53
    60.4 1909.08    84.4 1907.51    87.1 1907.08   93.32 1905.01    95.2 1904.25
   100.6 1903.97   104.1 1905.02   106.9 1906.25   115.4 1912.05   119.8 1913.45
   125.7 1914.25   160.7  1914.6   203.5 1913.91   225.1 1916.47   246.1 1918.03
   282.1 1919.62     305 1919.85   309.6 1922.77   320.1  1932.4   327.9 1939.01
   332.5 1943.78   336.5 1947.15   344.7 1950.65   355.4 1954.39   364.1 1957.93
#Mann= 5 ,-1,0
       0      .1       0      10     .06       0   93.32    .045       0
   104.1     .06       0  190.02     .07       0
Bank Sta=93.32,104.1
XS Rating Curve= 0 ,0
Exp/Cntr(USF)=0,0
Exp/Cntr=0.3,0.1

Type RM Length L Ch R = 1 ,6550    ,189.7,176.7,170.3
XS GIS Cut Line= 4
2221817.33353041699826.4263990422221860.58644087699802.127502547
2221999.08722926699928.8839886522222109.60893579699867.409663892
#Sta/Elev= 30
       0 1923.05     3.3 1920.47     7.8 1915.88    12.4 1913.12      17 1912.33
    35.2 1912.31    49.6  1913.7    54.5 1913.75      60 1912.76    62.8 1911.63
    74.1 1904.72    77.8 1903.81    81.6 1903.97    83.1 1904.71    88.3 1907.68
    93.9 1908.85   125.2 1907.58   184.5 1907.42     228 1908.55   237.4 1909.62
   243.2  1912.1   247.8 1912.81   269.7 1913.23   284.4 1912.72   294.4 1917.46
   334.7 1919.65   348.5 1921.71   358.5  1925.1   361.5 1926.71   363.8 1928.86
#Mann= 6 ,-1,0
       0      .1       0    74.1    .045       0    83.1      .1       0
   89.61     .06       0  139.61      .1       0  219.61     .07       0
Bank Sta=74.1,83.1
XS Rating Curve= 0 ,0
Exp/Cntr(USF)=0,0
Exp/Cntr=0.3,0.1

Type RM Length L Ch R = 1 ,6374    ,73.1,76,80.9
XS GIS Cut Line= 2
2221871.65887849699994.8078436622222127.50312161699893.824283384
#Sta/Elev= 30
       0 1927.97     4.9 1926.06    13.5 1921.65    23.2 1914.14    26.4 1912.31
    30.7 1910.86    39.3 1909.68      51 1909.03    90.9 1908.04   103.8 1907.34
   108.1 1906.51113.30181904.408   116.7 1903.59     121 1903.39  129.37 1904.41
   138.2 1906.29   146.8 1910.46   151.1 1911.76   155.8 1912.49   178.8 1912.96
     199 1912.45   202.1 1913.89     207 1917.15   211.3 1919.05   219.9 1920.59
   229.8 1923.51   241.4 1924.81   266.8 1929.25   271.5 1931.62   275.1  1934.2
#Mann= 4 ,-1,0
       0      .1       0113.3018    .045       0  129.37      .1       0
     130     .07       0
Bank Sta=113.3018,129.37
XS Rating Curve= 0 ,0
Exp/Cntr(USF)=0,0
Exp/Cntr=0.3,0.1

Type RM Length L Ch R = 1 ,6298    ,24,24.4,26.6
XS GIS Cut Line= 3
2221881.66407509700041.4112670712222039.48358196700017.487527645
2222085.01586022699963.466180553
#Sta/Elev= 30
       0 1932.28     2.5 1930.88    10.6 1926.77    18.7 1923.14    22.8 1920.87
      27 1917.67    30.9 1914.35      34 1912.24    37.5  1910.6      39 1910.12
      43 1909.59    63.2 1909.26    83.5 1908.12    95.6 1907.78   111.8 1905.85
   116.61904.326   119.9 1903.45   123.9 1903.28   140.1 1903.51  142.48 1904.33
   144.1 1904.89   148.2 1907.95   152.2 1909.52   163.2 1909.97     181 1910.07
   185.5 1910.28   197.9 1911.27   212.3 1911.93   222.8 1912.16   230.3 1912.11
#Mann= 3 ,-1,0
       0      .1       0   116.6    .045       0  142.48      .1       0
Bank Sta=116.6,142.48
XS Rating Curve= 0 ,0
Exp/Cntr(USF)=0,0
Exp/Cntr=0.3,0.1

Type RM Length L Ch R = 1 ,6273    ,26.9,26.7,27.5
XS GIS Cut Line= 3
2221882.04994186700066.1067400272222042.57051608700041.025400306
2222107.39613259699972.341116147
#Sta/Elev= 30
       0 1937.66     2.2 1936.64     6.2 1934.38    14.3 1929.45    18.3  1927.2
    27.2 1923.04    30.5 1921.12    34.5 1917.91    38.6 1915.42    46.7 1911.64
    50.7 1910.47    54.8 1909.74    62.9 1908.89    87.2 1908.37    99.3 1907.41
   111.5 1906.06  118.04 1903.82   119.6 1903.37   123.6 1903.25     131 1903.46
  133.45 1903.82   135.8 1904.15   139.2 1905.35   147.9 1907.92   167.8 1909.47
   177.6 1909.84   200.8 1910.21   234.2 1911.76   250.3 1911.83   256.9 1911.43
#Mann= 3 ,-1,0
       0      .1       0  118.04    .045       0  133.45      .1       0
Bank Sta=118.04,133.45
XS Rating Curve= 0 ,0
Exp/Cntr(USF)=0,0
Exp/Cntr=0.3,0.1

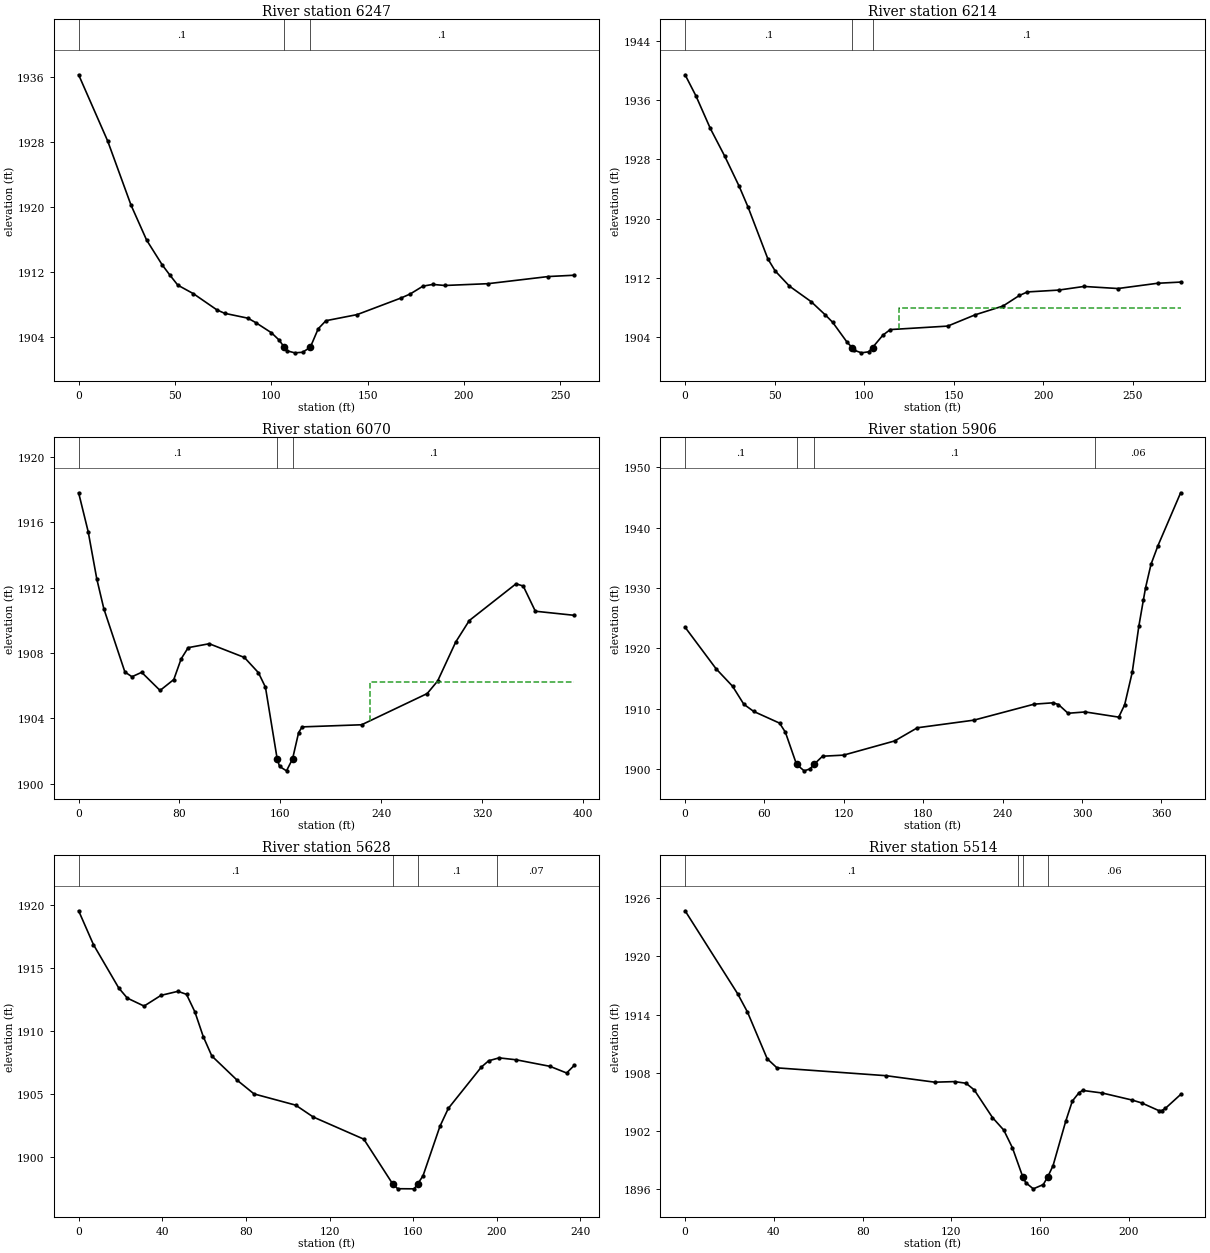
Type RM Length L Ch R = 1 ,6247    ,34.2,32.8,35.8
XS GIS Cut Line= 3
2221893.24007804700090.8022129842222052.60305196700066.492606792
2222118.58626877699996.650722338
#Sta/Elev= 30
       0 1936.24    15.1 1928.09    27.2 1920.22    35.3 1915.92    43.4 1912.87
    47.5 1911.58    51.5 1910.38    59.6 1909.33    71.8 1907.34    75.8 1906.92
    87.9 1906.32      92 1905.77   100.1 1904.53   104.1 1903.63  106.78 1902.75
   108.2 1902.31   112.2 1902.06   116.3 1902.13   120.3 1902.75   124.4 1905.02
   128.4 1906.01   144.6 1906.76   167.5 1908.81   172.2  1909.3   178.8 1910.26
   183.9 1910.47   190.1 1910.34   212.5 1910.56   243.9 1911.44   257.3  1911.6
#Mann= 3 ,-1,0
       0      .1       0  106.78    .045       0   120.3      .1       0
Bank Sta=106.78,120.3
XS Rating Curve= 0 ,0
Exp/Cntr(USF)=0,0
Exp/Cntr=0.3,0.1

Type RM Length L Ch R = 1 ,6214    ,149.9,143.7,137.9
XS GIS Cut Line= 3
2221890.15314392700113.5683521152222040.64118225700098.905415047
 2222127.0753376700007.840858521
#Sta/Elev= 30
       0 1939.41     6.1 1936.54    14.1 1932.16    22.1 1928.44    30.2 1924.36
    35.2 1921.53    46.2 1914.58    50.3 1912.94    58.3 1910.88    70.4 1908.79
    78.4 1906.98    82.4 1906.01    90.4 1903.34   93.24  1902.6    94.5 1902.23
    98.5 1901.88   102.5 1902.02   104.7  1902.6   110.5 1904.27   114.6 1905.02
   146.7 1905.49   162.1 1907.02   177.6  1908.2   186.7 1909.62   191.2  1910.1
   208.7 1910.35   222.8 1910.84   241.8 1910.56   263.9 1911.27   276.8 1911.43
#Mann= 3 ,-1,0
       0      .1       0   93.24    .045       0   104.7      .1       0
#XS Ineff= 2 , 0
                          119.47         1907.94
Permanent Ineff=
       F       F
Bank Sta=93.24,104.7
XS Rating Curve= 0 ,0
Exp/Cntr(USF)=0,0
Exp/Cntr=0.3,0.1

Type RM Length L Ch R = 1 ,6070    ,164.7,164.5,162.1
XS GIS Cut Line= 2
 2221915.7733432700335.4946962162222189.69110844700053.478492702
#Sta/Elev= 30
       0  1917.8     7.6 1915.41    14.4 1912.53      20  1910.7    36.7 1906.83
    42.3 1906.54      50 1906.81    64.6  1905.7    75.5 1906.37    81.3 1907.63
    86.9 1908.32   103.6 1908.56   131.5 1907.72   142.6 1906.79   148.2  1905.9
   157.5 1901.51   159.4 1901.05   164.9 1900.78   169.7 1901.51   174.5 1903.12
   177.3 1903.47   224.5  1903.6   276.5 1905.51   284.8 1906.28   299.1 1908.66
   309.9 1909.98     347 1912.23   352.7 1912.09   362.3 1910.55   393.1  1910.3
#Mann= 3 ,-1,0
       0      .1       0   157.5    .045       0   169.7      .1       0
#XS Ineff= 2 , 0
                          231.02         1906.22
Permanent Ineff=
       F       F
Bank Sta=157.5,169.7
XS Rating Curve= 0 ,0
Exp/Cntr(USF)=0,0
Exp/Cntr=0.3,0.1

Type RM Length L Ch R = 1 ,5906    ,282.4,277.5,269.4
XS GIS Cut Line= 2
2222092.25913246700395.6241872412222322.71905401 700100.30428777
#Sta/Elev= 30
       0 1923.49    23.4 1916.62    35.9 1913.72    44.4 1910.74    51.9 1909.55
    71.4 1907.62    75.8 1906.12   84.26 1900.78      90 1899.72    94.4 1900.04
    97.4 1900.78   103.9 1902.14   119.8 1902.32   158.4 1904.67   175.6 1906.85
   218.3 1908.11   263.9 1910.76   278.1 1910.98   282.2  1910.7   289.5 1909.25
   302.5 1909.47   327.8 1908.61   332.3 1910.67     338 1916.02     343 1923.66
   346.5 1928.08   348.1 1930.05   352.2 1933.91   357.5 1937.02   374.6 1945.75
#Mann= 4 ,-1,0
       0      .1       0   84.26    .045       0    97.4      .1       0
     310     .06       0
Bank Sta=84.26,97.4
XS Rating Curve= 0 ,0
Exp/Cntr(USF)=0,0
Exp/Cntr=0.3,0.1

Type RM Length L Ch R = 1 ,5628    ,111.3,114.2,117.9
XS GIS Cut Line= 2
2222356.98760472700448.2023731452222390.96797997 700213.60709022
#Sta/Elev= 30
       0 1919.54     7.1 1916.85    19.2 1913.41    23.3 1912.61    31.3 1911.98
    39.4 1912.83    47.5 1913.15    51.6 1912.91    55.6 1911.52    59.6 1909.56
    63.7 1908.02    75.8  1906.1    83.9 1905.01   103.8 1904.12   112.2 1903.18
   136.4 1901.42   150.2 1897.87   152.6 1897.49   160.5 1897.48  162.15 1897.87
   164.7 1898.51   172.8 1902.44   176.8 1903.86   192.6 1907.14   196.1 1907.64
   201.1 1907.87   209.2 1907.72   225.4  1907.2   233.4 1906.67     237 1907.27
#Mann= 4 ,-1,0
       0      .1       0   150.2    .045       0  162.15      .1       0
     200     .07       0
Bank Sta=150.2,162.15
XS Rating Curve= 0 ,0
Exp/Cntr(USF)=0,0
Exp/Cntr=0.3,0.1

Type RM Length L Ch R = 1 ,5514    ,119.4,127.8,141.1
XS GIS Cut Line= 2
2222412.50706744700486.5010969722222509.54109563700285.404751073
#Sta/Elev= 30
       0 1924.72    23.7 1916.14    28.1 1914.26      37 1909.43    41.4 1908.49
    90.6 1907.68   112.5 1907.01   121.4 1907.07   126.6  1906.9   130.3 1906.21
   138.5 1903.36   143.6 1902.06   147.5 1900.23152.11851897.259   153.5 1896.63
   156.9 1895.99   161.4 1896.43163.39841897.224   165.8 1898.38   171.5 1902.96
   174.5 1905.06   177.5 1905.92   179.1 1906.16     188 1905.89   201.5 1905.16
   205.8 1904.86   213.4 1904.08   214.7 1904.07   216.4  1904.3   223.3 1905.74
#Mann= 4 ,-1,0
       0      .1       0     150     .06       0152.1185    .045       0
163.3984     .06       0
Bank Sta=152.1185,163.3984
XS Rating Curve= 0 ,0
Exp/Cntr(USF)=0,0
Exp/Cntr=0.3,0.1

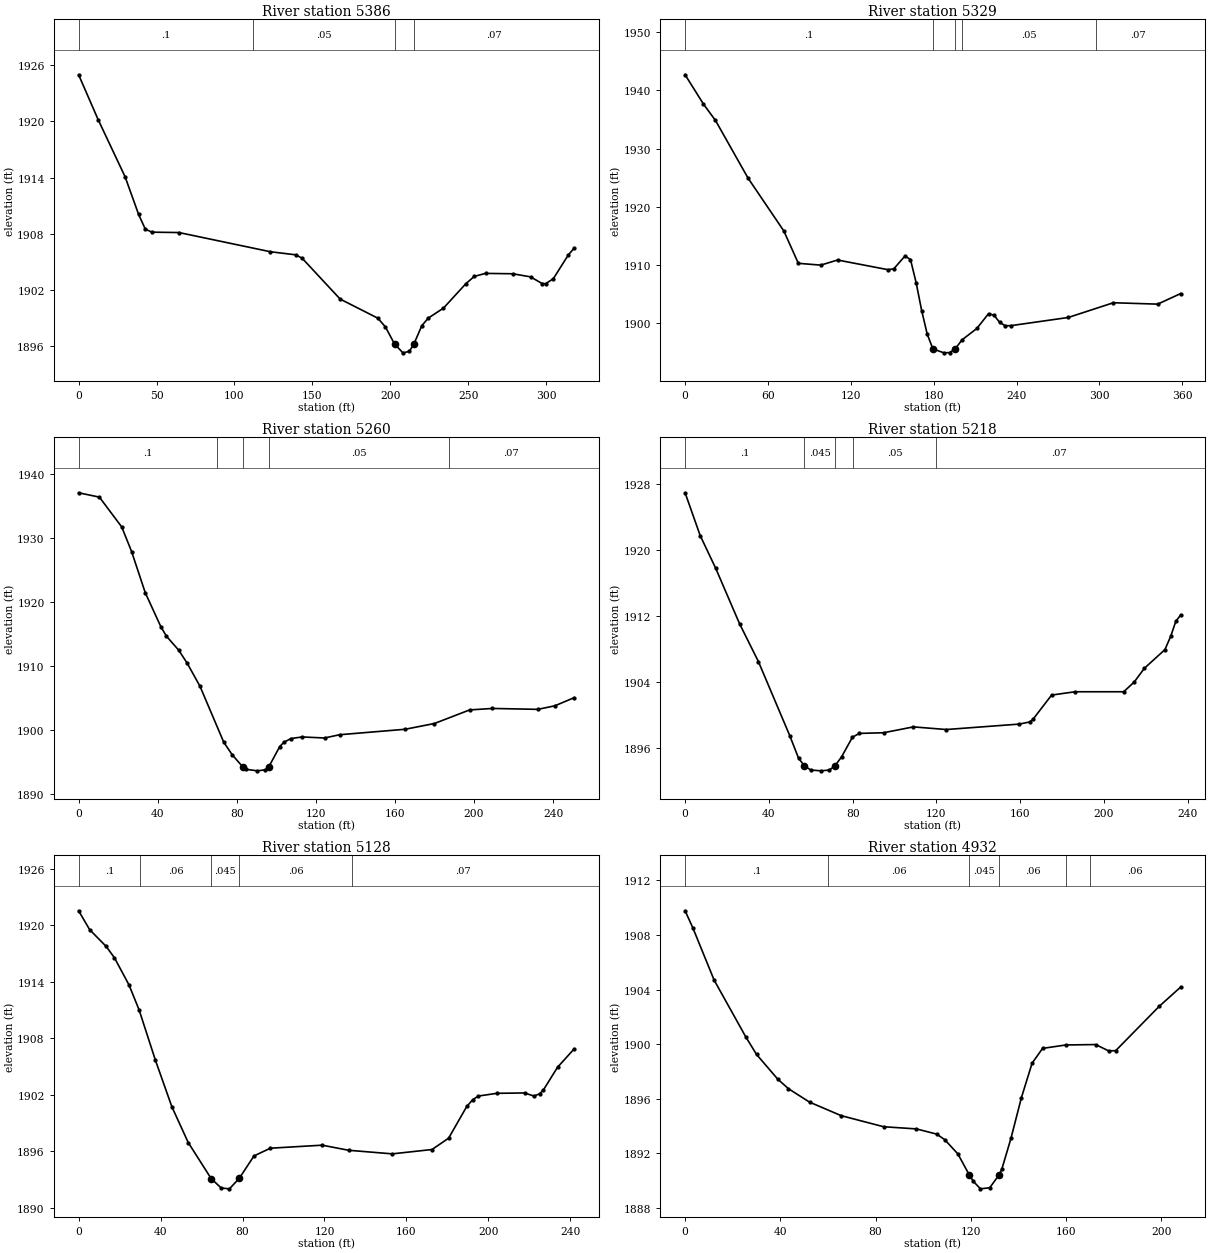
Type RM Length L Ch R = 1 ,5386    ,58.8,56.6,57.1
XS GIS Cut Line= 5
2222424.46579389 700492.747317132222455.64370928700416.934834937
2222532.92368297700430.7348302392222648.84364351700415.554835407
2222671.88208486700382.106257416
#Sta/Elev= 30
       0 1924.98    12.5  1920.2    29.8  1914.1    38.5 1910.07    42.8  1908.5
    47.1 1908.18    64.4 1908.14   123.1 1906.09   139.4 1905.76   143.5 1905.39
   167.8 1901.04     192    1899   196.9 1898.06  202.721896.246   208.1  1895.3
   212.2 1895.45  215.211896.266   220.2 1898.19   224.3    1899   234.1 1900.07
   248.5 1902.68   253.9 1903.46   261.1 1903.78   278.6 1903.74     290 1903.41
   297.4  1902.7   299.7 1902.68   304.6 1903.21   314.3 1905.76     318 1906.48
#Mann= 4 ,-1,0
       0      .1       0  111.97     .05       0  202.72    .045       0
  215.21     .07       0
Bank Sta=202.72,215.21
XS Rating Curve= 0 ,0
Exp/Cntr(USF)=0,0
Exp/Cntr=0.3,0.1

Type RM Length L Ch R = 1 ,5329    ,77.8,69,60.9
XS GIS Cut Line= 5
2222432.98639399 700545.480273182222464.16430938700469.667790987
2222541.44428307700483.4677862892222657.36424361700468.287791456
2222702.76730118700400.750636991
#Sta/Elev= 30
       0  1942.7    13.3 1937.65      22 1934.83    45.6 1924.89    71.5 1915.79
      82 1910.22    98.2 1909.91   110.4 1910.79     147 1909.12   151.1 1909.27
   159.2 1911.48   163.2 1910.87   167.3 1906.87   171.3 1902.07   175.3 1898.03
   179.4 1895.48   187.4  1894.8   191.5 1894.84   195.5 1895.48   200.6 1897.05
   211.3 1899.01   219.7 1901.55   223.7 1901.27   227.8 1900.04   231.8 1899.47
   235.8 1899.48   277.4 1900.89   310.1 1903.43   342.2 1903.19   358.8 1905.01
#Mann= 5 ,-1,0
       0      .1       0   179.4    .045       0   195.5      .1       0
  200.48     .05       0  297.39     .07       0
Bank Sta=179.4,195.5
XS Rating Curve= 0 ,0
Exp/Cntr(USF)=0,0
Exp/Cntr=0.3,0.1

Type RM Length L Ch R = 1 ,5260    ,44,42.2,40.5
XS GIS Cut Line= 3
2222548.39242697700596.185995697 2222652.2429884700491.859055546
2222712.26670739700407.540021725
#Sta/Elev= 30
       0 1937.04    10.5 1936.36    21.8 1931.71    26.8 1927.86    33.7 1921.44
    41.6 1916.13    44.4 1914.66    50.7 1912.44      55 1910.39    61.4 1906.83
    73.4 1898.11    77.6 1896.18   83.19 1894.19    84.7 1893.87    90.4 1893.63
    94.5 1893.79    96.1 1894.19   101.7  1897.4   103.8 1898.08   107.4 1898.67
   113.1 1898.92   124.4 1898.76   132.1 1899.27   165.2 1900.12     180 1901.02
   197.8 1903.14   209.3 1903.37   232.3 1903.23   240.9 1903.78   250.7 1905.05
#Mann= 5 ,-1,0
       0      .1       0      70     .05       0   83.19    .045       0
    96.1     .05       0   187.2     .07       0
Bank Sta=83.19,96.1
XS Rating Curve= 0 ,0
Exp/Cntr(USF)=0,0
Exp/Cntr=0.3,0.1

Type RM Length L Ch R = 1 ,5218    ,98.1,89.9,81.6
XS GIS Cut Line= 2
2222603.88233563700613.3230538012222744.88655847700423.314998343
#Sta/Elev= 30
       0 1926.97     7.2 1921.78    14.6 1917.82      26 1911.09      35  1906.5
      50  1897.5    54.2 1894.76 56.96971893.864      60 1893.35    64.9 1893.25
    68.9 1893.35   71.54 1893.86    74.7 1894.94    79.9 1897.33    83.2 1897.79
    94.8 1897.87     109 1898.58   124.7 1898.26   159.6 1898.92   164.6 1899.18
   166.1  1899.5     175 1902.44   186.2 1902.84   209.4 1902.84   214.4 1904.01
   219.3 1905.69   229.1 1907.95   231.9 1909.59   234.3 1911.39   236.6 1912.14
#Mann= 5 ,-1,0
       0      .1       0 56.9697    .045       0   71.54      .1       0
      80     .05       0     120     .07       0
Bank Sta=56.9697,71.54
XS Rating Curve= 0 ,0
Exp/Cntr(USF)=0,0
Exp/Cntr=0.3,0.1

Type RM Length L Ch R = 1 ,5128    ,188.2,195.9,200.1
XS GIS Cut Line= 3
2222720.84152439700678.5995146292222713.69584355700565.221378757
2222773.71956255700451.843242886
#Sta/Elev= 30
       0 1921.52     5.4 1919.51    13.4 1917.75    17.5 1916.53    24.6 1913.65
    29.5 1911.02    37.5 1905.66    45.5 1900.74    53.5 1896.94    64.71893.117
    69.6 1892.12    73.6 1892.03   78.37 1893.13    85.6 1895.52    93.6 1896.34
   118.9 1896.66   131.8 1896.12   153.1 1895.74   172.5  1896.2   180.6  1897.4
   189.5 1900.78   192.4 1901.48   195.1 1901.87   204.2 1902.16   217.7  1902.2
   222.3 1901.87     225 1902.11   226.8 1902.49   233.8 1904.93   241.9 1906.87
#Mann= 5 ,-1,0
       0      .1       0      30     .06       0    64.7    .045       0
   78.37     .06       0   133.6     .07       0
Bank Sta=64.7,78.37
XS Rating Curve= 0 ,0
Exp/Cntr(USF)=0,0
Exp/Cntr=0.3,0.1

Type RM Length L Ch R = 1 ,4932    ,91.8,102,110.5
XS GIS Cut Line= 2
2222801.10880183700700.120424254 2222892.6752648700513.084432252
#Sta/Elev= 30
       0 1909.78     3.3 1908.51    12.2  1904.7    25.5 1900.54      30 1899.26
    38.9 1897.45    43.4 1896.75    52.3 1895.76    65.6 1894.77    83.4 1893.96
    97.2  1893.8   105.7 1893.42   109.1 1893.01   114.6 1891.97  119.31 1890.46
   121.1 1889.96   124.1 1889.41     128 1889.49131.98981890.451   133.1 1890.87
   136.9  1893.1   141.3 1896.09   145.8 1898.62   150.2  1899.7     160 1899.95
   172.5 1899.98   177.9 1899.52   180.9 1899.53   199.2 1902.78   208.2 1904.19
#Mann= 6 ,-1,0
       0      .1       0      60     .06       0  119.31    .045       0
131.9898     .06       0     160      .1       0     170     .06       0
Bank Sta=119.31,131.9898
XS Rating Curve= 0 ,0
Exp/Cntr(USF)=0,0
Exp/Cntr=0.3,0.1

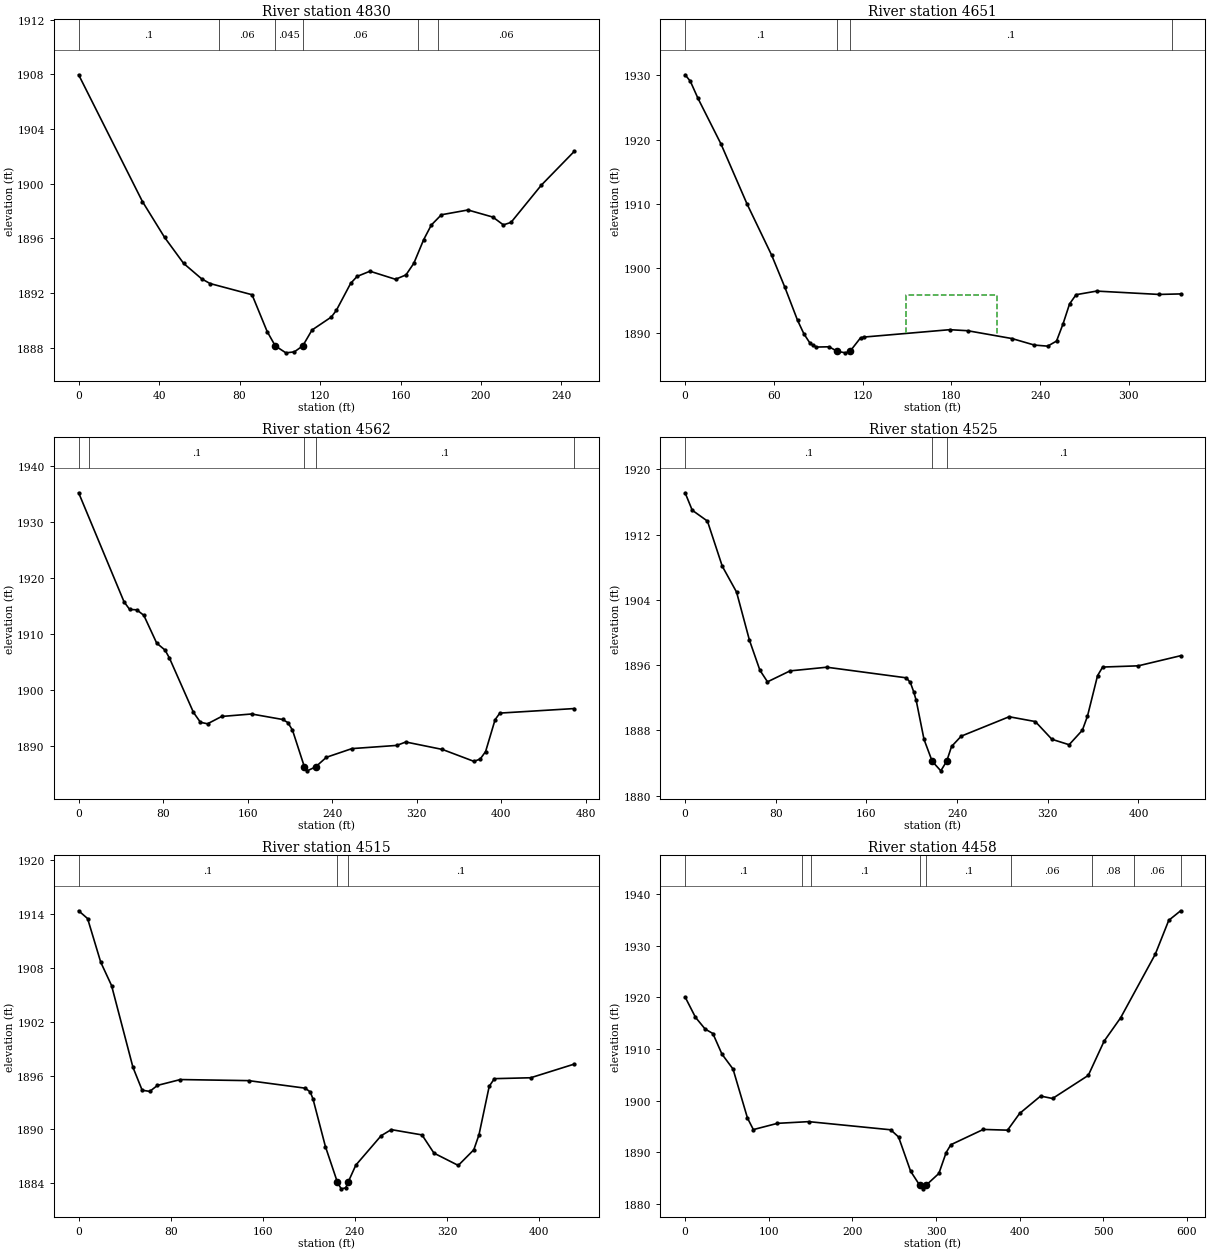
Type RM Length L Ch R = 1 ,4830    ,180.6,179.6,178.5
XS GIS Cut Line= 3
2222809.92828076700700.4441836742222961.27380079700652.853949331
2222997.71677304700573.108151243
#Sta/Elev= 30
       0 1907.96    31.7 1898.69    42.7 1896.07    52.2 1894.16    61.1 1893.04
    65.3 1892.69    86.2 1891.87    93.7 1889.18   97.73 1888.13     103 1887.62
   107.2 1887.69   111.4 1888.13     116 1889.29   125.6 1890.24   128.1 1890.73
   135.2  1892.7   138.4 1893.21   144.8 1893.59   157.5    1893   162.7 1893.32
   166.6 1894.17   171.5  1895.9   175.3 1896.97   180.3 1897.72   193.5 1898.07
   205.9 1897.55   211.1 1896.98   214.9 1897.16     230 1899.89   246.3 1902.35
#Mann= 6 ,-1,0
       0      .1       0      70     .06       0   97.73    .045       0
   111.4     .06       0  168.65      .1       0  178.65     .06       0
Bank Sta=97.73,111.4
XS Rating Curve= 0 ,0
Exp/Cntr(USF)=0,0
Exp/Cntr=0.3,0.1

Type RM Length L Ch R = 1 ,4651    ,106.1,88.4,73.5
XS GIS Cut Line= 3
2222892.89522238700861.1230214882223032.86822963700809.368296119
2223111.67656145700641.165438668
#Sta/Elev= 30
       0 1930.11     3.5 1929.12     8.7 1926.45    24.3 1919.33    41.9 1910.01
    58.6 1902.02    67.5 1897.04      76 1891.95    80.3 1889.84    84.5 1888.36
    86.6 1888.03    88.8 1887.78    97.3 1887.82  102.83 1887.12   108.4 1886.88
   111.5 1887.12   118.6 1889.21   120.8 1889.33   178.9 1890.48     191 1890.32
     221  1889.1   236.1 1888.09   245.1 1887.92   251.1 1888.71   255.5 1891.38
   259.9 1894.48   264.3 1895.92   278.2 1896.48   320.3 1895.96     335 1896.04
#Mann= 4 ,-1,0
       0      .1       0  102.83    .045       0   111.5      .1       0
  329.23     .06       0
#XS Ineff= 1 ,-1
  149.39  210.62 1895.88
Permanent Ineff=
       F
Bank Sta=102.83,111.5
XS Rating Curve= 0 ,0
Exp/Cntr(USF)=0,0
Exp/Cntr=0.3,0.1

Type RM Length L Ch R = 1 ,4562    ,37.1,37.8,37.9
XS GIS Cut Line= 4
2222959.30297614701048.4620256812223074.66844764700893.565728278
2223036.57597908 700810.397469072223121.79483937700646.840774464
#Sta/Elev= 30
       0 1935.28      43  1915.8    48.3 1914.45      55 1914.38    61.7  1913.4
    73.9 1908.43    81.8 1907.19    85.9 1905.79   108.7 1896.06   115.3  1894.3
     122 1894.03   135.4 1895.34   163.7 1895.78   193.1  1894.8     198 1894.25
   202.4 1892.91  213.68 1886.35   216.4 1885.63   224.4 1886.35   234.5 1888.05
   258.7  1889.6   301.1 1890.17   309.7 1890.78   344.3 1889.45   374.2 1887.32
   380.1 1887.74   385.2 1889.07   394.2 1894.77   398.7 1895.94     469 1896.75
#Mann= 5 ,-1,0
       0     .08       0      10      .1       0  213.68    .045       0
   224.4      .1       0  469.04     .06       0
Bank Sta=213.68,224.4
XS Rating Curve= 0 ,0
Exp/Cntr(USF)=0,0
Exp/Cntr=0.3,0.1

Type RM Length L Ch R = 1 ,4525    ,10.5,10,9.4
XS GIS Cut Line= 4
2222988.40879717701029.0023715682223105.38623894700873.914632023
2223066.74663148700790.8130104922223135.02758166700655.839039216
#Sta/Elev= 30
       0 1917.13     6.3 1914.99    19.7 1913.66    32.8 1908.13    45.4 1904.96
    56.8 1899.05      66 1895.38    72.7 1893.96    92.6  1895.3     125 1895.75
   195.1 1894.45   198.7 1893.89   201.7 1892.73   203.9 1891.68   210.8  1886.9
     218 1884.22   225.6 1883.05  230.76 1884.22   235.1 1886.04   243.6  1887.3
   285.9 1889.68     309 1889.09   323.6 1886.92   338.8 1886.25   350.5 1888.03
     355 1889.75   363.9 1894.72   368.4 1895.77   399.8 1895.92   437.2 1897.16
#Mann= 3 ,-1,0
       0      .1       0     218    .045       0  230.76      .1       0
Bank Sta=218,230.76
XS Rating Curve= 0 ,0
Exp/Cntr(USF)=0,0
Exp/Cntr=0.3,0.1

Type RM Length L Ch R = 1 ,4515    ,46.1,56.4,64.9
XS GIS Cut Line= 4
  2222998.994991701026.8851328032223114.91381339700872.856012641
2223076.27420592700788.6957717272223142.43791733700659.544207055
#Sta/Elev= 30
       0 1914.37     7.8  1913.5    19.2 1908.64    28.6 1906.04    47.2 1896.92
    55.2 1894.37    61.8 1894.24    68.5 1894.91    88.4 1895.56   147.7 1895.44
   196.8  1894.6   201.2 1894.18   203.6  1893.4   214.4 1888.09   224.8 1884.12
   228.1 1883.38     232 1883.49   234.1 1884.12   240.8 1886.02   262.8  1889.3
   271.6 1889.98   298.3 1889.39   308.7 1887.36   329.8 1885.99   343.3 1887.73
   347.8  1889.4   356.7 1894.81   361.2 1895.66   392.7 1895.76   430.5 1897.28
#Mann= 3 ,-1,0
       0      .1       0   224.8    .045       0   234.1      .1       0
Bank Sta=224.8,234.1
XS Rating Curve= 0 ,0
Exp/Cntr(USF)=0,0
Exp/Cntr=0.3,0.1

Type RM Length L Ch R = 1 ,4458    ,128.6,129,129.2
XS GIS Cut Line= 3
2222994.41327869701068.6688181312223266.36067812700665.769951281
2223365.39231174700627.056073126
#Sta/Elev= 30
       0 1920.09    12.4 1916.16      24 1913.88    33.2 1913.02    44.1 1909.02
    57.3 1906.14    74.6 1896.64    81.6 1894.42   110.4 1895.63   147.8 1895.96
   245.8 1894.38   255.2 1892.99   269.6 1886.36  280.231883.708   284.1 1882.95
   288.5 1883.71   303.4 1885.93   312.1 1889.98   317.7 1891.49   356.5 1894.45
   385.5 1894.31   399.9 1897.54     425 1900.91   439.3 1900.44     482 1904.91
   500.9 1911.53   520.7 1916.07   562.1 1928.37   578.2 1934.93   592.4 1936.78
#Mann= 9 ,-1,0
       0      .1       0     140     .05       0     150      .1       0
  280.23    .045       0   288.5      .1       0     390     .06       0
  486.09     .08       0  536.09     .06       0  592.42      .1       0
Bank Sta=280.23,288.5
XS Rating Curve= 0 ,0
Exp/Cntr(USF)=0,0
Exp/Cntr=0.3,0.1