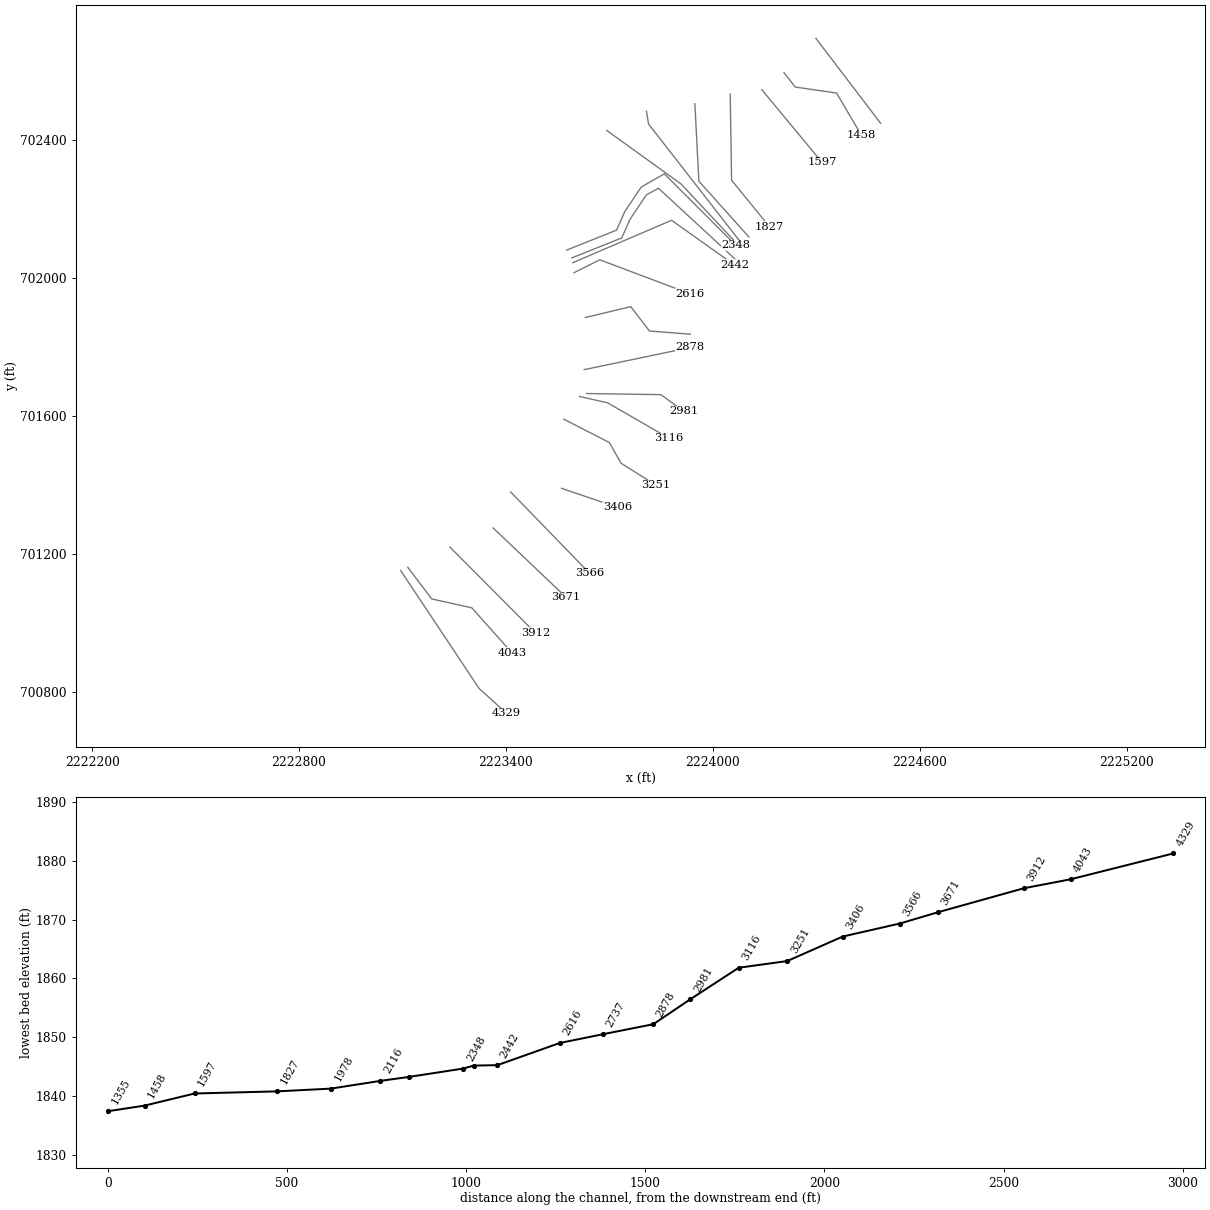
HEC-RAS study GUMRN.prj: GUMRN

--- GUMRN.g01 (geometry) --- (continued)

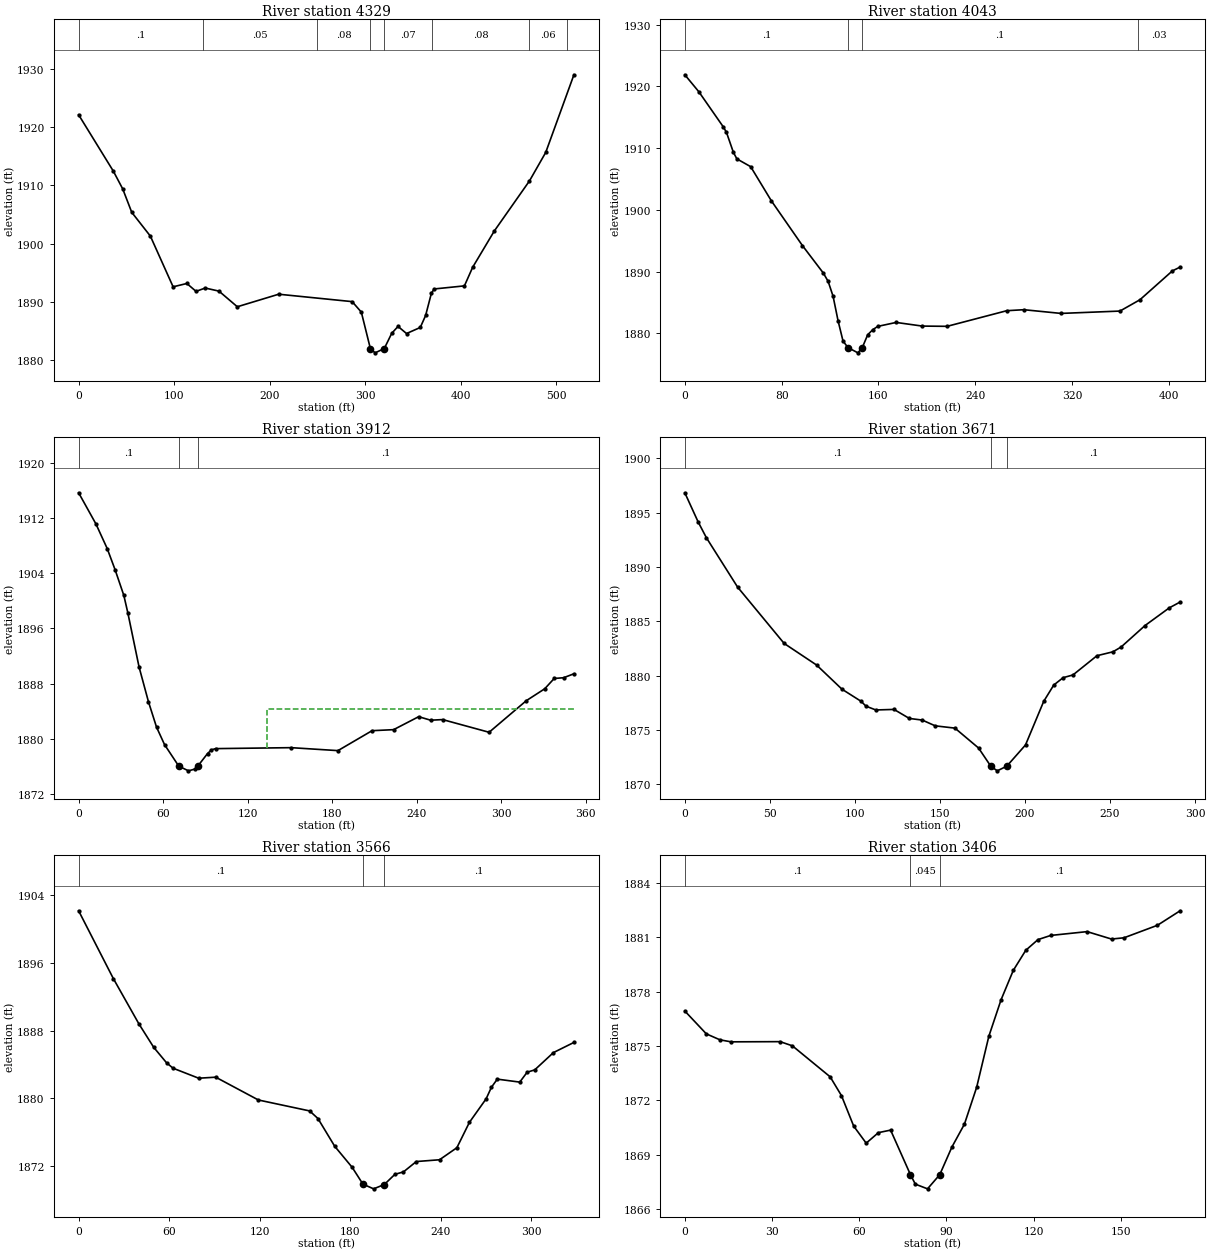
Type RM Length L Ch R = 1 ,4329    ,274.8,286.7,295
XS GIS Cut Line= 3
2223094.58366493 701151.475237612223322.37107939 700809.29635009
2223402.08271959700737.462483209
#Sta/Elev= 30
       0 1922.08    36.4  1912.4    46.2 1909.36    55.6 1905.36    75.1 1901.28
    98.9 1892.59   113.3 1893.16   122.9 1891.81   132.5 1892.38   146.9 1891.85
   166.1 1889.17   209.4 1891.32   286.3 1890.05   295.9 1888.25  305.36    1882
   310.3 1881.27   319.9    1882   327.7 1884.61   334.3  1885.8   343.2 1884.58
   357.6 1885.62   363.2 1887.68   369.2 1891.47   372.1 1892.22   403.8 1892.75
   412.4 1895.93     435 1902.14   471.9 1910.75   488.9 1915.63   518.4 1928.94
#Mann= 8 ,-1,0
       0      .1       0     130     .05       0     250     .08       0
  305.36    .045       0   319.9     .07       0     370     .08       0
  471.06     .06       0  511.06     .08       0
Bank Sta=305.36,319.9
XS Rating Curve= 0 ,0
Exp/Cntr(USF)=0,0
Exp/Cntr=0.3,0.1

Type RM Length L Ch R = 1 ,4043    ,137.3,130.8,124.8
XS GIS Cut Line= 4
2223115.39358853701160.6002489622223184.73315809701069.029672371
2223301.18129017701043.0934974982223417.62942225700912.354003752
#Sta/Elev= 30
       0 1921.87    11.6 1919.12    31.6 1913.49    34.4 1912.56    40.1 1909.33
      43 1908.26    54.4    1907    71.5 1901.47    97.2 1894.22   114.4 1889.79
   118.4 1888.44   122.5 1886.02   126.6 1882.07   130.7 1878.78   134.8 1877.72
     143 1876.87  146.63 1877.72   151.1  1879.8   155.3 1880.62   159.4 1881.15
   174.6 1881.79   196.2  1881.2   216.7 1881.16     266 1883.69   280.1 1883.85
   310.8 1883.25   359.5 1883.63     376 1885.46   402.8 1890.13   409.2 1890.75
#Mann= 4 ,-1,0
       0      .1       0   134.8    .045       0  146.63      .1       0
  374.16     .03       0
Bank Sta=134.8,146.63
XS Rating Curve= 0 ,0
Exp/Cntr(USF)=0,0
Exp/Cntr=0.3,0.1

Type RM Length L Ch R = 1 ,3912    ,246.5,240.8,242.5
XS GIS Cut Line= 2
2223237.13986273701219.5487667712223485.32451073700970.557367222
#Sta/Elev= 30
       0 1915.65    12.3 1911.13    20.3 1907.56    25.9 1904.49    32.1 1900.77
    34.9 1898.28    42.9  1890.4    49.6 1885.34    55.3 1881.68      61 1879.14
    71.1 1876.02      78 1875.34    82.4 1875.59   84.58 1876.02    91.5 1877.84
    94.3 1878.38    97.2 1878.56   150.9  1878.7   184.1 1878.27   208.3 1881.16
   223.6 1881.31   241.4 1883.19   249.9 1882.68   258.4 1882.77   291.4 1880.93
   317.8 1885.51   330.9 1887.24   337.6 1888.73   344.3 1888.84   351.6 1889.41
#Mann= 3 ,-1,0
       0      .1       0    71.1    .045       0   84.58      .1       0
#XS Ineff= 2 , 0
                          133.66         1884.36
Permanent Ineff=
       F       F
Bank Sta=71.1,84.58
XS Rating Curve= 0 ,0
Exp/Cntr(USF)=0,0
Exp/Cntr=0.3,0.1

Type RM Length L Ch R = 1 ,3671    ,107.1,105.1,104.9
XS GIS Cut Line= 2
2223362.98813984701274.559875216 2223574.0585476701073.944967533
#Sta/Elev= 30
       0 1896.82     7.8 1894.15    12.7 1892.68      31 1888.15    58.4 1882.96
    77.5 1880.97    92.4 1878.75   103.7 1877.63   106.5 1877.19   112.3 1876.84
     123 1876.89     132 1876.06   139.6 1875.91   147.2 1875.38   158.8 1875.17
   172.7 1873.34  179.88 1871.67   183.7 1871.24   189.3 1871.67   200.3 1873.62
     211 1877.63   216.9 1879.13   222.4 1879.81   228.2 1880.06   242.3 1881.83
   251.7 1882.19   256.5 1882.63   270.6 1884.61   284.8 1886.23   291.2 1886.77
#Mann= 3 ,-1,0
       0      .1       0  179.88    .045       0   189.3      .1       0
Bank Sta=179.88,189.3
XS Rating Curve= 0 ,0
Exp/Cntr(USF)=0,0
Exp/Cntr=0.3,0.1

Type RM Length L Ch R = 1 ,3566    ,154.6,159.8,164.8
XS GIS Cut Line= 2
2223413.47313604701379.0153791542223642.30584424701143.402928741
#Sta/Elev= 30
       0 1902.14      23 1894.15      40 1888.79    49.8 1886.03    58.3 1884.21
    62.6 1883.57    79.6 1882.39    90.9 1882.51   119.2 1879.82   153.2 1878.53
   158.7 1877.63   169.8 1874.36   181.4 1871.87188.50961869.894   195.6 1869.34
202.67961869.849   209.7 1871.05   215.4 1871.34   223.9 1872.56   239.3 1872.77
   250.8 1874.19   259.1 1877.18   270.2 1879.96   273.7 1881.32   277.6 1882.28
   292.5 1881.93   297.4  1883.1   302.4 1883.37   314.8 1885.41   328.4 1886.61
#Mann= 3 ,-1,0
       0      .1       0188.5096    .045       0202.6796      .1       0
Bank Sta=188.5096,202.6796
XS Rating Curve= 0 ,0
Exp/Cntr(USF)=0,0
Exp/Cntr=0.3,0.1

Type RM Length L Ch R = 1 ,3406    ,163.5,154.8,146.6
XS GIS Cut Line= 2
 2223561.1424553701389.5219709442223722.49276509701334.662865614
#Sta/Elev= 30
       0 1876.93     7.4 1875.67    12.1 1875.34    15.9 1875.23    32.8 1875.24
      37 1875.01      50  1873.3    53.9 1872.26    58.1 1870.58    62.4 1869.64
    66.6 1870.22    70.8 1870.36   77.63  1867.9    79.3 1867.38    83.5 1867.12
    87.7  1867.9    91.9 1869.43    96.2 1870.69   100.4 1872.72   104.6 1875.54
   108.8 1877.55     113 1879.17   117.3 1880.28   121.5 1880.87   125.9  1881.1
   138.4 1881.31   146.8  1880.9   151.1 1880.97   162.6 1881.66   170.4 1882.46
#Mann= 3 ,-1,0
       0      .1       0   77.63    .045       0    87.7      .1       0
Bank Sta=77.63,87.7
XS Rating Curve= 0 ,0
Exp/Cntr(USF)=0,0
Exp/Cntr=0.3,0.1

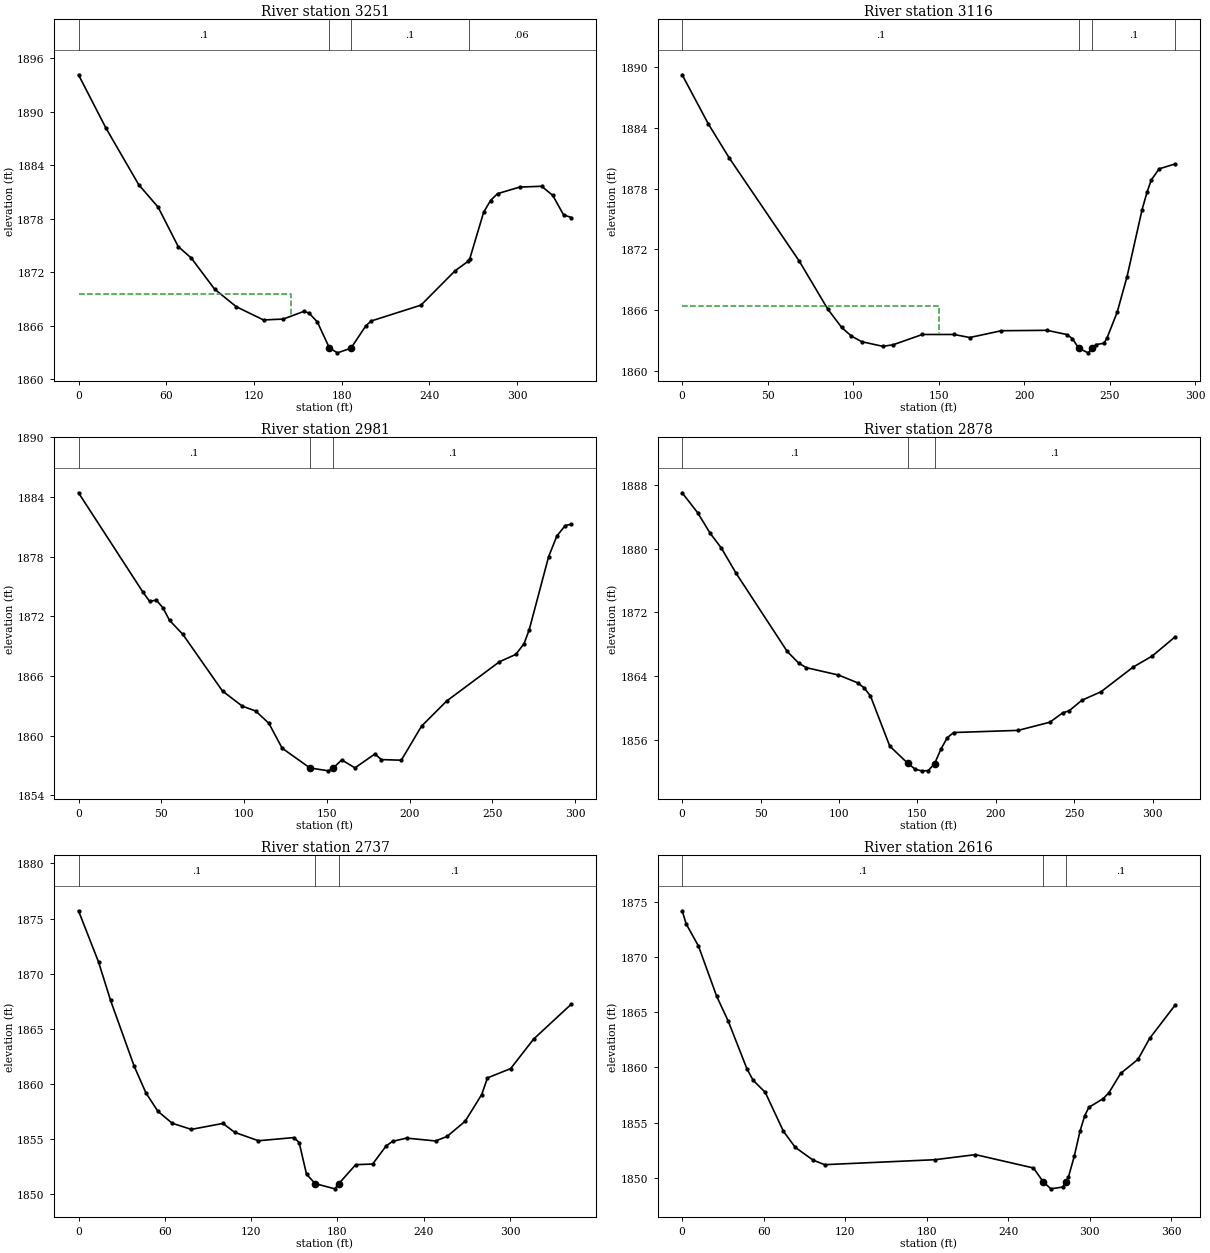
Type RM Length L Ch R = 1 ,3251    ,129.9,135.3,139.2
XS GIS Cut Line= 4
  2223567.465563701589.7780024792223699.61085684 701522.21888628
2223733.64430551701462.1394309782223835.08724888701398.299442044
#Sta/Elev= 30
       0 1894.15    18.8 1888.16    41.2 1881.82    54.5 1879.29    68.2 1874.88
    77.2 1873.58    93.1  1870.1     108 1868.12   126.6 1866.64   140.1 1866.74
   154.2  1867.6   157.7 1867.42   163.4 1866.42   171.7 1863.49   177.2 1862.95
   186.4 1863.47   196.5 1865.96   200.2 1866.52   234.3  1868.3   257.7 1872.16
   266.4  1873.2   267.7  1873.5   277.2 1878.72   281.9 1880.04   286.7 1880.81
   301.9 1881.55   316.9 1881.64   324.5 1880.61   331.9 1878.43   337.3 1878.13
#Mann= 4 ,-1,0
       0      .1       0   171.7    .045       0   186.4      .1       0
  267.46     .06       0
#XS Ineff= 2 , 0
          145.16 1869.52
Permanent Ineff=
       F       F
Bank Sta=171.7,186.4
XS Rating Curve= 0 ,0
Exp/Cntr(USF)=0,0
Exp/Cntr=0.3,0.1

Type RM Length L Ch R = 1 ,3116    ,130.6,134.8,136.4
XS GIS Cut Line= 3
2223613.34602595 701655.659384822223694.93572569701637.028665983
2223872.24877393 701534.88093167
#Sta/Elev= 30
       0 1889.22    15.2 1884.41    27.5 1881.03    68.5 1870.85    85.1 1866.14
    93.3 1864.31      99 1863.46     105 1862.91   117.4 1862.45   123.5 1862.61
   140.5 1863.62     159 1863.62   168.2 1863.32   186.7 1863.99   213.4 1864.03
   225.1 1863.61   228.2 1863.21  232.12 1862.24   237.5 1861.81   239.7 1862.25
   242.1 1862.63   246.7 1862.75   248.5 1863.28   254.4  1865.8   260.2 1869.32
     269 1875.93   271.9 1877.65   274.4 1878.86     279 1879.95   288.3 1880.43
#Mann= 4 ,-1,0
       0      .1       0  232.12    .045       0   239.7      .1       0
  288.32     .06       0
#XS Ineff= 2 , 0
           150.5  1866.4
Permanent Ineff=
       F       F
Bank Sta=232.12,239.7
XS Rating Curve= 0 ,0
Exp/Cntr(USF)=0,0
Exp/Cntr=0.3,0.1

Type RM Length L Ch R = 1 ,2981    ,100.8,103.6,106.5
XS GIS Cut Line= 3
2223633.22862522701664.1339654862223849.50456508701660.799314431
2223915.24482873701612.685063494
#Sta/Elev= 30
       0 1884.42      39 1874.41      43  1873.5      47 1873.63      51 1872.85
      55 1871.59      63 1870.19      87 1864.48      99 1862.96     107 1862.48
     115 1861.24     123 1858.74   139.8 1856.75     151 1856.46  153.93 1856.75
     159 1857.56     167 1856.76     179 1858.15     183 1857.59     195 1857.53
   207.2 1860.95   222.4 1863.48   254.3 1867.43   264.2 1868.17   269.2 1869.26
   272.3 1870.67     284    1878     289 1880.08     294 1881.12   297.8 1881.27
#Mann= 3 ,-1,0
       0      .1       0   139.8    .045       0  153.93      .1       0
Bank Sta=139.8,153.93
XS Rating Curve= 0 ,0
Exp/Cntr(USF)=0,0
Exp/Cntr=0.3,0.1

Type RM Length L Ch R = 1 ,2878    ,153,140.4,123.3
XS GIS Cut Line= 2
2223626.60639682701733.2152585822223934.37251265701797.439631032
#Sta/Elev= 30
       0 1886.97     9.8  1884.5    17.9  1881.9      25 1880.06    34.3 1876.94
      67 1867.13    74.4 1865.66    79.2  1865.1    99.7 1864.18   111.9 1863.21
     116 1862.59   120.1 1861.56   132.4 1855.29143.9096 1853.14   148.7 1852.39
   152.8  1852.2   156.9 1852.22     161  1853.1     165  1854.9   169.1 1856.35
   173.2 1856.99   214.3 1857.26   234.5 1858.28   242.7 1859.45   246.8 1859.71
   254.9 1861.02   267.2  1862.1   287.6 1865.17   299.9 1866.57   314.4 1868.96
#Mann= 3 ,-1,0
       0      .1       0143.9096    .045       0     161      .1       0
Bank Sta=143.9096,161
XS Rating Curve= 0 ,0
Exp/Cntr(USF)=0,0
Exp/Cntr=0.3,0.1

Type RM Length L Ch R = 1 ,2737    ,113.8,120.9,128.3
XS GIS Cut Line= 4
2223630.50954173701884.3509754022223761.85676142701915.717475626
2223816.09466806701845.1428501222223934.37251265701835.994287557
#Sta/Elev= 30
       0 1875.71      14 1871.04    22.3 1867.58    38.7 1861.62    46.9 1859.19
    55.2 1857.53    65.1 1856.45    78.4 1855.89   100.4 1856.43   108.6 1855.62
   125.1 1854.86   149.9 1855.15   153.4 1854.69   158.5 1851.83   164.51850.975
   178.2  1850.5  180.95 1850.97   192.7 1852.69   204.5 1852.75   213.9  1854.4
   218.4 1854.81   228.1  1855.1   248.2 1854.84   256.2 1855.25   268.8 1856.63
   280.3 1859.05   284.3 1860.56   300.4  1861.4   316.4 1864.08   342.7 1867.26
#Mann= 3 ,-1,0
       0      .1       0   164.5    .045       0  180.95      .1       0
Bank Sta=164.5,180.95
XS Rating Curve= 0 ,0
Exp/Cntr(USF)=0,0
Exp/Cntr=0.3,0.1

Type RM Length L Ch R = 1 ,2616    ,163.2,174.1,183.7
XS GIS Cut Line= 3
2223597.47023844702014.2185123172223671.99021308702051.478499633
 2223933.7190439701952.965194642
#Sta/Elev= 30
       0  1874.2       3    1873      12 1871.01    25.4 1866.46      34 1864.18
    47.7 1859.88    52.2 1858.85    61.2 1857.74    74.6 1854.21    83.3 1852.76
    96.3 1851.61   104.9 1851.19   186.1 1851.64     216  1852.1   258.7 1850.89
  265.821849.643   271.5    1849   280.1 1849.16   282.61849.652   284.4 1850.05
   288.7 1851.94   292.9  1854.2   296.4 1855.62   299.5 1856.39     310 1857.17
   314.3 1857.72   322.9 1859.46   335.7 1860.74   344.2 1862.63     363 1865.65
#Mann= 3 ,-1,0
       0      .1       0  265.82    .045       0   282.6      .1       0
Bank Sta=265.82,282.6
XS Rating Curve= 0 ,0
Exp/Cntr(USF)=0,0
Exp/Cntr=0.3,0.1

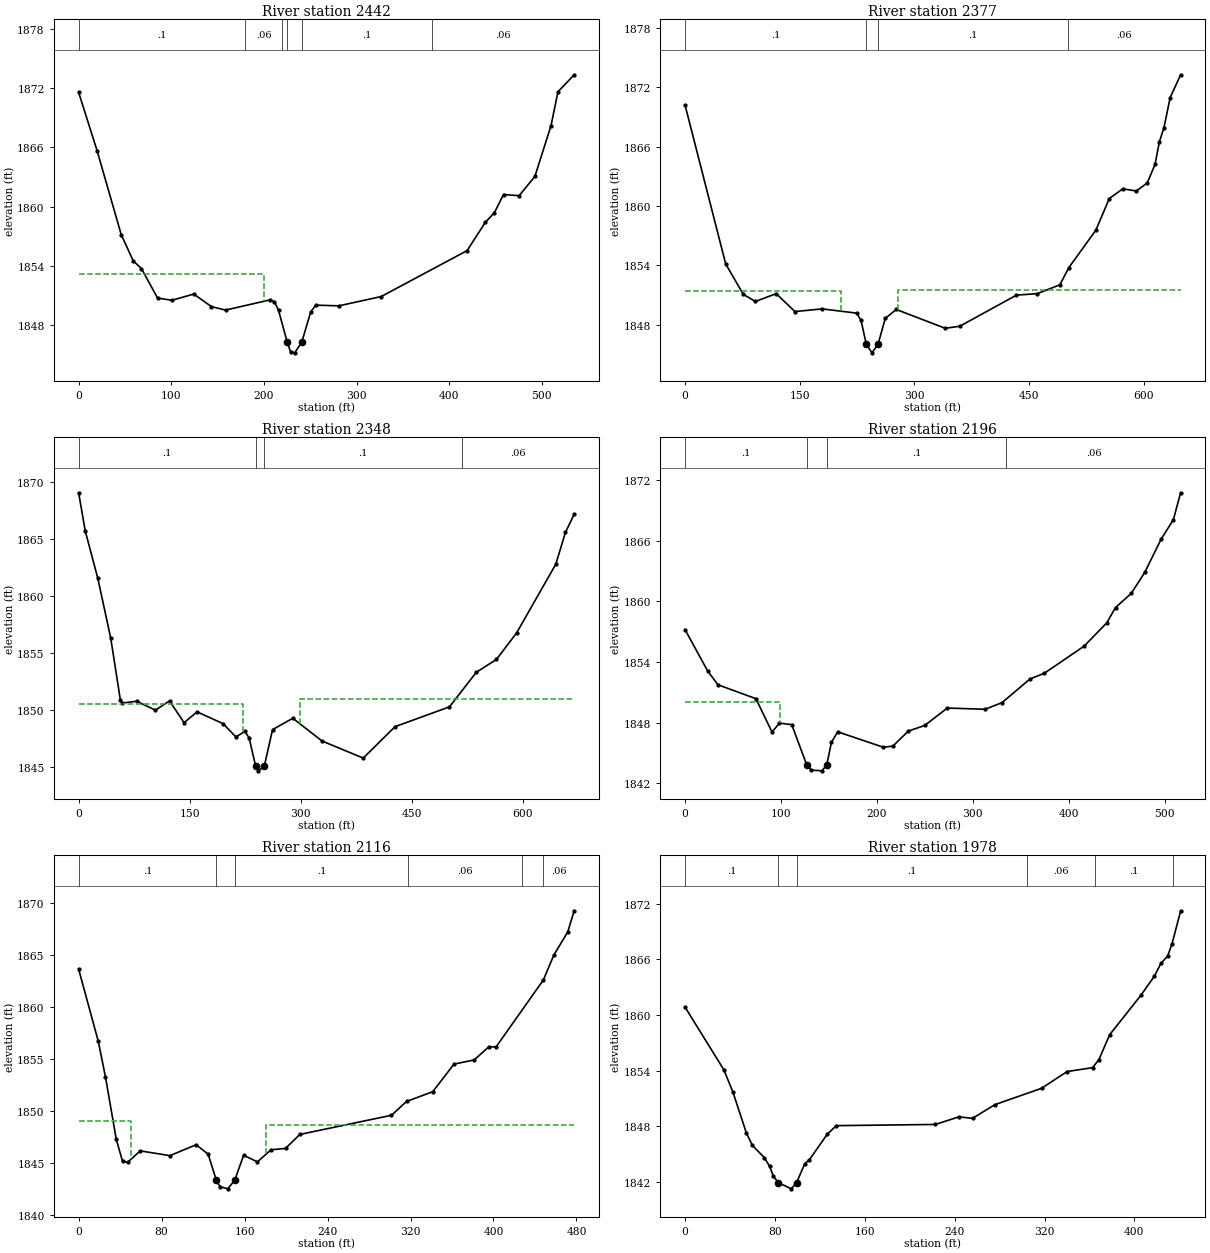
Type RM Length L Ch R = 1 ,2442    ,59.4,65.7,73.9
XS GIS Cut Line= 3
2223593.91529147702043.1438827862223880.13460601702165.996008664
2224062.45238856 702036.60919524
#Sta/Elev= 30
       0 1871.55    19.9 1865.67      46 1857.17      59 1854.52    67.8 1853.75
    85.2 1850.77   100.7 1850.54   124.3 1851.17   143.4  1849.9   158.6 1849.55
     207 1850.59   211.4 1850.39   215.8 1849.53  225.26 1846.28   228.8 1845.35
   233.2 1845.23   240.8 1846.28   250.6 1849.37   256.1 1850.05     281 1849.98
   326.7 1850.92   419.4 1855.56     439 1858.41   448.9  1859.4   458.7 1861.23
   475.6 1861.11   492.6 1863.06     510 1868.19   517.5 1871.61     535 1873.33
#Mann= 6 ,-1,0
       0      .1       0     180     .06       0     220      .1       0
  225.26    .045       0   240.8      .1       0  381.47     .06       0
#XS Ineff= 2 , 0
             200 1853.16
Permanent Ineff=
       F       F
Bank Sta=225.26,240.8
XS Rating Curve= 0 ,0
Exp/Cntr(USF)=0,0
Exp/Cntr=0.3,0.1

Type RM Length L Ch R = 1 ,2377    ,28,28.9,26.8
XS GIS Cut Line= 6
2223590.84776211702056.9236608912223735.71459279702114.870393165
2223759.25545278702168.2900369812223807.24259044702239.818034632
2223842.23341824702258.7885718262224068.26282702702049.845875055
#Sta/Elev= 30
       0 1870.17    53.1 1854.14    76.1 1851.07    91.9 1850.35   119.2 1851.14
   143.6 1849.33   179.4  1849.6   224.4 1849.17   230.1 1848.44  236.931846.052
   244.4 1845.16  252.391846.034   261.8 1848.64   276.2 1849.54   340.3 1847.64
   359.3 1847.85   433.4 1850.99   460.6 1851.14   490.1 1852.03   501.8 1853.76
   537.2 1857.55   554.8 1860.75   572.5 1861.73   590.2 1861.51   604.5 1862.33
   614.6  1864.2   620.3 1866.48   626.2 1867.88   634.4 1870.95   648.1 1873.25
#Mann= 4 ,-1,0
       0      .1       0  236.93    .045       0  252.39      .1       0
  500.34     .06       0
#XS Ineff= 2 , 0
          204.07  1851.4     278         1851.51
Permanent Ineff=
       F       F
Bank Sta=236.93,252.39
XS Rating Curve= 0 ,0
Exp/Cntr(USF)=0,0
Exp/Cntr=0.3,0.1

Type RM Length L Ch R = 1 ,2348    ,171,152.1,135.6
XS GIS Cut Line= 6
2223575.90837019702079.5591031852223720.77520088 702137.50583546
2223744.31606086702190.9254792762223792.30319853702262.453476927
2223859.30410772702300.4810199822224065.73934145702094.045786254
#Sta/Elev= 30
       0 1869.08     8.9 1865.74    25.9 1861.57    43.4  1856.3    56.3 1850.92
    58.2 1850.61    78.4 1850.77   103.7 1849.99   122.8  1850.8   142.5 1848.89
     160 1849.84     195 1848.81   212.5 1847.64   224.6 1848.12   230.3 1847.56
  239.221845.058   242.9 1844.66   250.8 1845.06     262 1848.28   289.4 1849.28
   328.8 1847.28   384.5 1845.78   427.5 1848.54     501 1850.28   537.2 1853.31
   564.4 1854.44   591.6 1856.76   644.7 1862.81   657.7  1865.6   669.5 1867.19
#Mann= 4 ,-1,0
       0      .1       0  239.22    .045       0   250.8      .1       0
  517.58     .06       0
#XS Ineff= 2 , 0
          222.55 1850.53  298.79         1851.01
Permanent Ineff=
       F       F
Bank Sta=239.22,250.8
XS Rating Curve= 0 ,0
Exp/Cntr(USF)=0,0
Exp/Cntr=0.3,0.1

Type RM Length L Ch R = 1 ,2196    ,84,79.3,73.8
XS GIS Cut Line= 3
2223692.30671038702426.1330456292223907.47428524702271.236748227
2224079.49949835702087.671218744
#Sta/Elev= 30
       0 1857.19    23.5 1853.11    34.3 1851.74    73.8 1850.37    90.6 1847.07
    98.4 1847.95   111.2  1847.8   126.7 1843.85   131.7  1843.3   142.8 1843.23
  147.76 1843.85   152.6 1846.05   159.1 1847.09   206.8 1845.56   216.7 1845.68
   232.7 1847.16   249.9 1847.72   273.4 1849.44   312.9 1849.32   330.5 1849.98
   359.7 1852.32   374.6 1852.88     416 1855.56   439.7 1857.87   448.8 1859.38
   465.2 1860.78   479.3 1862.86   496.3 1866.13   509.1 1868.07   516.7 1870.73
#Mann= 4 ,-1,0
       0      .1       0   126.7    .045       0  147.76      .1       0
  335.12     .06       0
#XS Ineff= 2 , 0
           99.01 1850.04
Permanent Ineff=
       F       F
Bank Sta=126.7,147.76
XS Rating Curve= 0 ,0
Exp/Cntr(USF)=0,0
Exp/Cntr=0.3,0.1

Type RM Length L Ch R = 1 ,2116    ,143.7,138.5,131.8
XS GIS Cut Line= 3
2223807.34691841702482.0315501822223813.38303635702444.808822853
2224084.00232423702097.732040999
#Sta/Elev= 30
       0 1863.68    18.9 1856.76    25.9 1853.31    36.3 1847.31    42.3 1845.22
    47.4 1845.12    59.4 1846.21      88 1845.75   113.3  1846.8   124.9 1845.89
  132.711843.401   136.3 1842.77   143.8 1842.56  150.55  1843.4   159.1 1845.79
   172.4 1845.15   185.4 1846.31   199.5 1846.45   213.3 1847.79   301.6 1849.63
   316.2 1850.96   341.5  1851.9   361.9 1854.55   381.4 1854.95   395.7 1856.23
   402.4 1856.19   448.1 1862.64   458.2 1865.03   471.6 1867.26   477.8 1869.29
#Mann= 6 ,-1,0
       0      .1       0  132.71    .045       0  150.55      .1       0
  317.71     .06       0  427.71      .1       0  447.71     .06       0
#XS Ineff= 2 , 0
           50.61 1849.04  180.42         1848.71
Permanent Ineff=
       F       F
Bank Sta=132.71,150.55
XS Rating Curve= 0 ,0
Exp/Cntr(USF)=0,0
Exp/Cntr=0.3,0.1

Type RM Length L Ch R = 1 ,1978    ,142.7,150.3,138.6
XS GIS Cut Line= 3
2223947.71655307702503.6543656232223959.29208225702279.273449535
2224103.89558543 702118.10780037
#Sta/Elev= 30
       0 1860.84    34.5 1854.09    42.5 1851.71    54.5 1847.29    59.9 1845.93
    70.6  1844.6    75.2 1843.68    78.6  1842.6      831841.903    94.6 1841.24
    99.3 1841.92   106.6 1843.96   110.6 1844.37   126.6 1847.14   134.7 1848.06
   222.8 1848.19   243.8 1849.01   255.9 1848.85   275.9 1850.33   317.4 1852.09
   340.1  1853.9   362.8 1854.32   368.4 1855.18     378 1857.87   405.7 1862.11
   417.7 1864.17   423.7 1865.58   429.6 1866.36   433.6 1867.71   441.2 1871.25
#Mann= 6 ,-1,0
       0      .1       0      83    .045       0    99.3      .1       0
  304.68     .06       0  364.68      .1       0  434.68     .06       0
Bank Sta=83,99.3
XS Rating Curve= 0 ,0
Exp/Cntr(USF)=0,0
Exp/Cntr=0.3,0.1

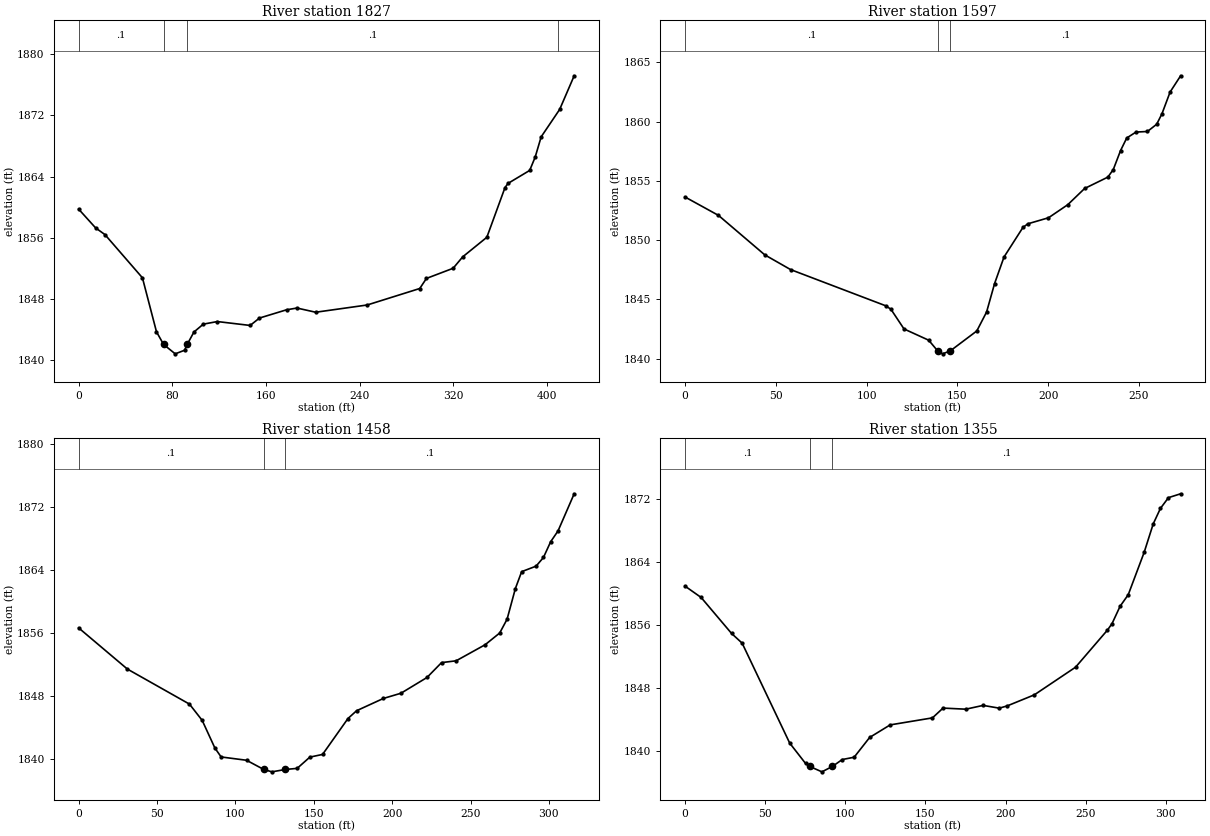
Type RM Length L Ch R = 1 ,1827    ,223.7,229.9,247.5
XS GIS Cut Line= 3
2224050.14851412702531.6320232972224054.17259275702282.139148225
2224163.82873542702147.332514114
#Sta/Elev= 30
       0 1859.73    14.5 1857.27    22.5 1856.39    54.5 1850.73    66.5 1843.66
   72.561842.003    82.5 1840.77    90.5 1841.24   92.791842.019    98.5 1843.63
   106.5 1844.66   118.5    1845   146.5 1844.49   154.5 1845.46   177.6 1846.54
   186.5 1846.77   202.5 1846.22   246.5 1847.17   291.4 1849.33   297.1 1850.65
   319.9 1851.98   328.1 1853.48   348.7 1856.04   364.2 1862.55   366.8  1863.1
   385.3  1864.8     390 1866.55   395.1  1869.2   410.9 1872.79   423.3  1877.2
#Mann= 4 ,-1,0
       0      .1       0   72.56    .045       0   92.79      .1       0
  409.53     .05       0
Bank Sta=72.56,92.79
XS Rating Curve= 0 ,0
Exp/Cntr(USF)=0,0
Exp/Cntr=0.3,0.1

Type RM Length L Ch R = 1 ,1597    ,132.9,139.5,148
XS GIS Cut Line= 2
2224141.59275973 702544.452911372224315.84720933702334.339683597
#Sta/Elev= 30
       0 1853.64    18.4 1852.09    43.9 1848.76    58.1 1847.52   110.6 1844.46
   113.4 1844.17   120.6 1842.51   134.2 1841.56  139.09 1840.67   141.9 1840.41
   146.2 1840.67   160.7 1842.34   166.1 1843.94   170.5 1846.34   175.7 1848.58
   186.1 1851.07   188.8 1851.38   200.2 1851.89   210.8 1852.99   220.1 1854.36
   232.9 1855.32   235.9 1855.96   239.9 1857.56   243.3 1858.62   248.4 1859.12
   254.7 1859.17   259.8 1859.78   262.7 1860.66   267.2  1862.5     273 1863.87
#Mann= 3 ,-1,0
       0      .1       0  139.09    .045       0   146.2      .1       0
Bank Sta=139.09,146.2
XS Rating Curve= 0 ,0
Exp/Cntr(USF)=0,0
Exp/Cntr=0.3,0.1

Type RM Length L Ch R = 1 ,1458    ,112,103,94.1
XS GIS Cut Line= 4
2224206.18370822702593.7952365142224238.47159939702551.979770903
2224358.62489931702534.5125510912224430.61101733702412.242012405
#Sta/Elev= 30
       0 1856.63    31.1  1851.4    70.7 1846.95    78.8 1844.89    86.9 1841.38
    90.9 1840.24   107.1 1839.82   118.1 1838.65   123.3 1838.35   131.9 1838.65
   139.4 1838.79   147.5 1840.22   155.6 1840.56   171.8 1845.12   177.3 1846.11
   194.4 1847.67   205.6 1848.33   222.2 1850.33   231.5 1852.22   240.8 1852.45
   259.3 1854.49   268.6 1855.98   273.3 1857.73   278.6 1861.63   282.6 1863.77
   291.8 1864.47   296.5 1865.57   301.1 1867.57   305.8 1868.94   316.1 1873.66
#Mann= 3 ,-1,0
       0      .1       0   118.1    .045       0   131.9      .1       0
Bank Sta=118.1,131.9
XS Rating Curve= 0 ,0
Exp/Cntr(USF)=0,0
Exp/Cntr=0.3,0.1

Type RM Length L Ch R = 1 ,1355    ,134.1,123.7,117
XS GIS Cut Line= 2
2224298.57326955702693.0919683352224486.11520571702447.176052046
#Sta/Elev= 30
       0 1860.92      10 1859.49      29 1854.93    35.6  1853.7    65.3 1841.03
    75.2 1838.45   77.831838.069    85.4 1837.39   91.931838.074    98.1 1838.95
   105.5 1839.24   115.2 1841.75     128 1843.34   154.4 1844.23     161 1845.47
   175.2 1845.33     186 1845.81   196.1 1845.46   201.1 1845.75     218 1847.15
   243.7 1850.65   263.6 1855.35   266.5 1856.18   271.5 1858.37   276.6 1859.84
   286.5 1865.19   292.2 1868.82   296.7 1870.78   301.7 1872.14   309.3 1872.63
#Mann= 3 ,-1,0
       0      .1       0   77.83    .045       0   91.93      .1       0
Bank Sta=77.83,91.93
XS Rating Curve= 0 ,0
Exp/Cntr(USF)=0,0
Exp/Cntr=0.3,0.1