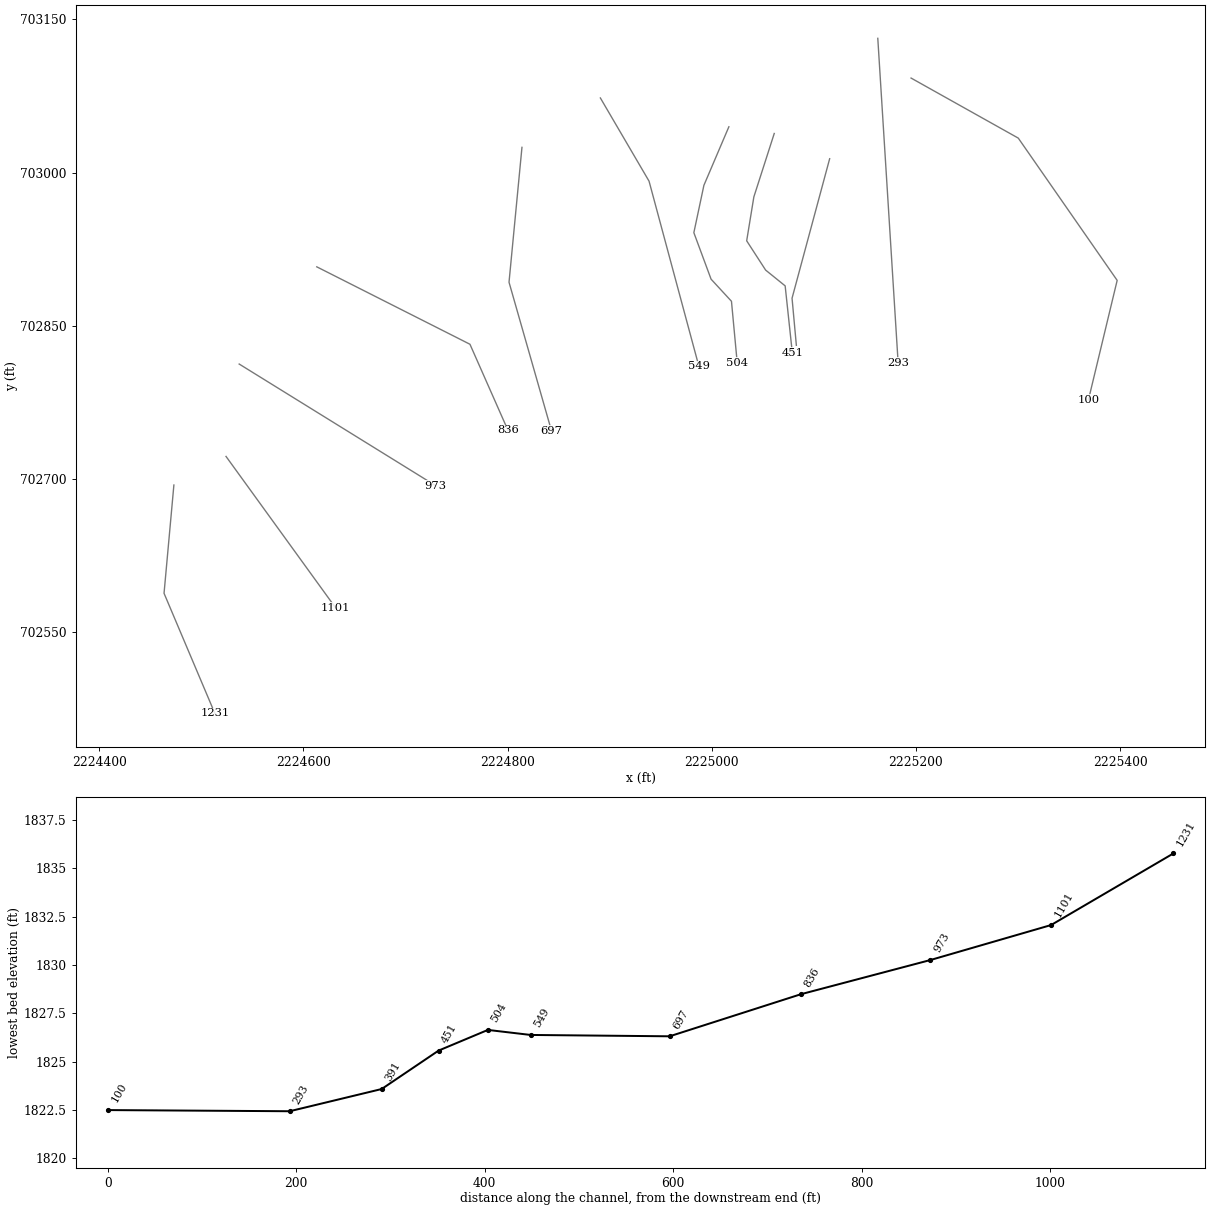
HEC-RAS study GUMRN.prj: GUMRN

--- GUMRN.g01 (geometry) --- (continued)

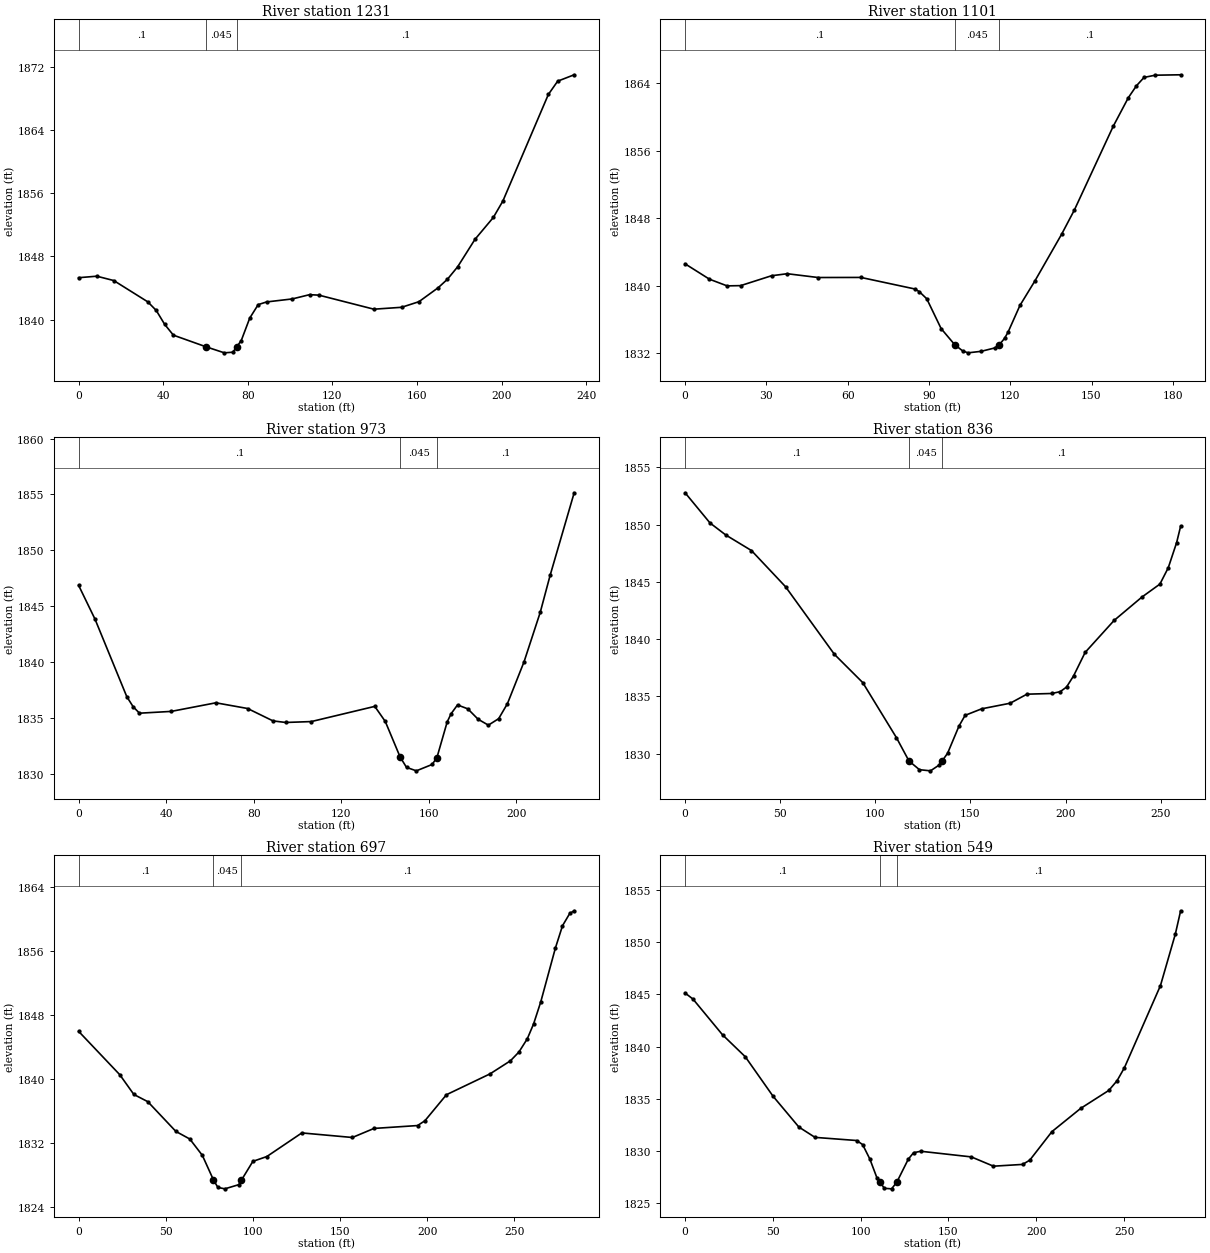
Type RM Length L Ch R = 1 ,1231    ,117.1,129.9,136.9
XS GIS Cut Line= 3
2224473.07488731702693.7548424032224463.42821819702587.641482043
2224513.20503087702469.952118736
#Sta/Elev= 30
       0  1845.3     8.6 1845.49    16.6 1844.94    32.7 1842.24    36.7 1841.15
    40.7 1839.38    44.8 1838.02    60.21836.549    68.9 1835.78    72.9 1835.86
    74.71836.526    76.9 1837.34    80.9 1840.18    84.9 1841.89    88.9 1842.23
     101 1842.61   109.2 1843.15   113.6 1843.09   139.6 1841.31   152.7 1841.55
   160.9 1842.26     170 1844.03   174.4 1845.11   179.2 1846.68   187.4 1850.16
   196.1 1852.94   200.6 1855.02   222.1 1868.52   226.5  1870.2   234.3 1871.01
#Mann= 3 ,-1,0
       0      .1       0    60.2    .045       0    74.7      .1       0
Bank Sta=60.2,74.7
XS Rating Curve= 0 ,0
Exp/Cntr(USF)=0,0
Exp/Cntr=0.3,0.1

Type RM Length L Ch R = 1 ,1101    ,122.3,128,132.6
XS GIS Cut Line= 2
2224524.16174147702721.7659112662224631.34695396702573.612128676
#Sta/Elev= 30
       0 1842.61       9 1840.79    15.5    1840    20.5 1840.03    31.9  1841.2
    37.7 1841.44    49.1 1840.99    64.9    1841    84.7 1839.64    86.4 1839.33
    89.2 1838.47    94.5 1834.94    99.5 1833.04   102.4 1832.31   104.4 1832.07
   109.3 1832.25   114.3 1832.65     116 1833.04   117.9 1833.78   119.2 1834.52
   123.6 1837.69   129.1 1840.58     139 1846.13   143.7    1849     158 1858.89
   163.6 1862.29   166.6  1863.7   169.4 1864.69   173.5 1864.95   182.9    1865
#Mann= 3 ,-1,0
       0      .1       0    99.5    .045       0     116      .1       0
Bank Sta=99.5,116
XS Rating Curve= 0 ,0
Exp/Cntr(USF)=0,0
Exp/Cntr=0.3,0.1

Type RM Length L Ch R = 1 ,973     ,136.4,137.4,138
XS GIS Cut Line= 2
2224537.03718838702812.3239277482224729.54712285702693.091968335
#Sta/Elev= 30
       0 1846.86     7.5 1843.83      22  1836.9    24.9    1836    27.8 1835.42
    42.3 1835.58    62.7 1836.35    77.2 1835.84    88.8 1834.73    94.6 1834.59
   106.3 1834.67   135.3 1836.03   140.1 1834.68   146.9 1831.49   149.8 1830.57
   154.3 1830.26   161.5 1830.83   163.7 1831.45   168.4 1834.65   170.2 1835.38
   173.1 1836.16   177.8 1835.81   182.5 1834.88   187.2 1834.35   191.9 1834.93
   195.9 1836.27   203.5 1840.02   210.9 1844.45   215.4 1847.75   226.4 1855.15
#Mann= 3 ,-1,0
       0      .1       0   146.9    .045       0   163.7      .1       0
Bank Sta=146.9,163.7
XS Rating Curve= 0 ,0
Exp/Cntr(USF)=0,0
Exp/Cntr=0.3,0.1

Type RM Length L Ch R = 1 ,836     ,153.9,139.4,121.6
XS GIS Cut Line= 3
2224613.05401103 702907.595957682224763.11330851702831.708827242
2224800.41376245702747.246879804
#Sta/Elev= 30
       0 1852.79    13.1 1850.15    21.4  1849.1    34.9 1847.74    52.8 1844.58
    78.5 1838.67    93.4  1836.2   111.1 1831.39   117.7 1829.35   123.2 1828.59
     129 1828.49   133.5 1828.99   135.1 1829.35     138 1830.03     144 1832.41
   147.2 1833.34   155.9 1833.91   170.9  1834.4   179.7 1835.19   192.8 1835.25
   197.2 1835.41   200.5 1835.81   204.2 1836.78   210.3 1838.84   225.5 1841.63
   240.1 1843.67   249.6 1844.81     254 1846.24   258.4 1848.44   260.5 1849.87
#Mann= 3 ,-1,0
       0      .1       0   117.7    .045       0   135.1      .1       0
Bank Sta=117.7,135.1
XS Rating Curve= 0 ,0
Exp/Cntr(USF)=0,0
Exp/Cntr=0.3,0.1

Type RM Length L Ch R = 1 ,697     ,142.3,147.5,151.5
XS GIS Cut Line= 3
2224814.06022608703024.6934354562224801.38437839702892.502452455
2224843.03359221702746.730204076
#Sta/Elev= 30
       0 1845.97    23.6 1840.56    31.7 1838.09    39.7 1837.19    55.8 1833.48
    63.8 1832.53      71 1830.49   77.341827.442    79.9 1826.49    83.9 1826.31
    91.9 1826.83   93.471827.409     100 1829.74     108 1830.34   128.1 1833.29
   157.1 1832.72   169.5 1833.85   194.5 1834.21   198.7  1834.8   211.1 1838.06
   236.1 1840.66   247.8 1842.29   252.7 1843.39   257.5 1845.04   261.1 1846.89
   265.2 1849.63   273.6 1856.35   277.7 1859.15   281.9  1860.7   284.4 1861.02
#Mann= 3 ,-1,0
       0      .1       0   77.34    .045       0   93.47      .1       0
Bank Sta=77.34,93.47
XS Rating Curve= 0 ,0
Exp/Cntr(USF)=0,0
Exp/Cntr=0.3,0.1

Type RM Length L Ch R = 1 ,549     ,50.6,45.4,41.2
XS GIS Cut Line= 3
2224890.87808179703073.0899257572224938.56136619702991.563074295
2224987.34477302702810.271784745
#Sta/Elev= 30
       0 1845.14     4.5 1844.56    21.3 1841.14    34.3 1839.03    50.1 1835.25
    64.8  1832.3      74 1831.31    97.7 1831.01   101.1 1830.62   105.2 1829.24
   109.3 1827.41   110.8 1827.05   113.5 1826.43   117.6 1826.38   120.6 1827.03
   127.1 1829.22   130.1 1829.84   134.2 1829.98     163 1829.44   175.6 1828.55
   192.2 1828.72   196.3 1829.13   208.9 1831.86   225.3 1834.09   241.3 1835.81
     246 1836.74   250.2 1837.99   270.7 1845.85   279.2  1850.8   282.2 1853.02
#Mann= 3 ,-1,0
       0      .1       0   110.8    .045       0   120.6      .1       0
Bank Sta=110.8,120.6
XS Rating Curve= 0 ,0
Exp/Cntr(USF)=0,0
Exp/Cntr=0.3,0.1

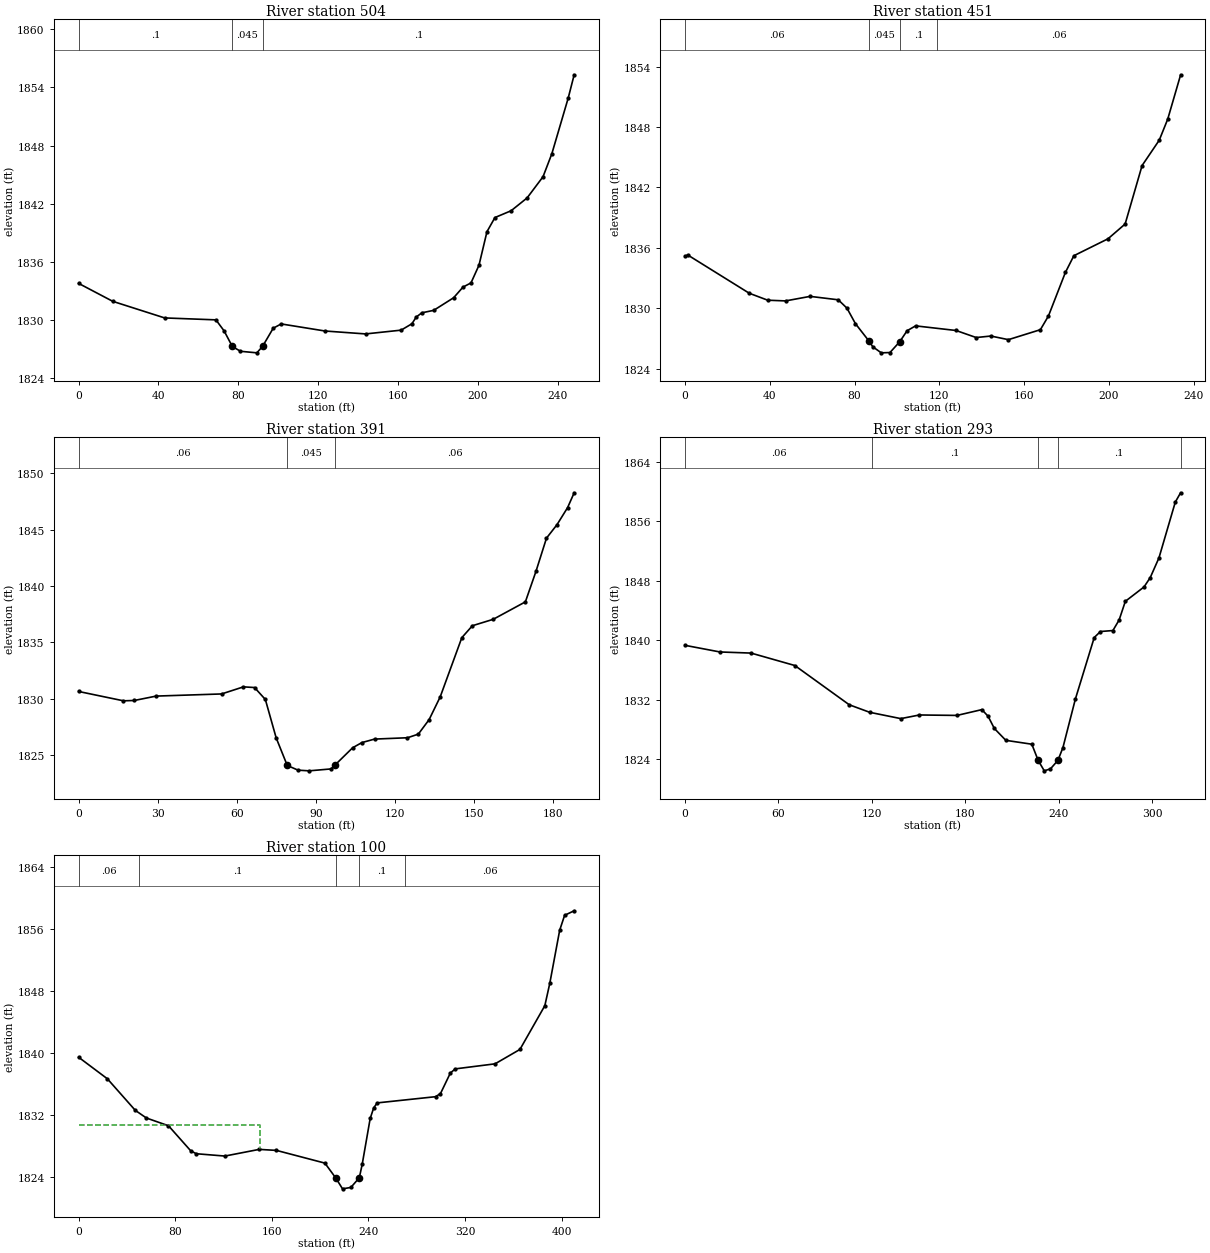
Type RM Length L Ch R = 1 ,504     ,51.6,52.3,52.7
XS GIS Cut Line= 6
2225016.77050733703044.865998781 2224992.2976795702987.481436966
2224982.45228899702941.0674531442224999.33010129702895.497359938
2225019.30217918702873.8375008212225024.92811661702813.639970289
#Sta/Elev= 30
       0  1833.8    17.1 1831.95    43.1 1830.24    68.8 1830.04    72.9  1828.9
      77  1827.3    81.1  1826.8    89.3 1826.64   92.15  1827.3    97.5 1829.18
   101.5 1829.62   123.5 1828.89   143.8 1828.59   161.6 1828.98     167 1829.64
   169.2 1830.34     172 1830.77   177.9 1831.02   187.9 1832.32   192.6 1833.42
   196.6 1833.85   200.6 1835.67   204.6 1839.13   208.6 1840.59   216.7 1841.29
   224.7 1842.61   232.7  1844.8   237.1 1847.16   245.3  1852.9   248.3 1855.31
#Mann= 3 ,-1,0
       0      .1       0      77    .045       0   92.15      .1       0
Bank Sta=77,92.15
XS Rating Curve= 0 ,0
Exp/Cntr(USF)=0,0
Exp/Cntr=0.3,0.1

Type RM Length L Ch R = 1 ,451     ,61.2,60.4,59.3
XS GIS Cut Line= 6
2225061.21005379703038.3001756572225041.23797591702976.133567024
2225034.20555412702933.0951456622225052.77114764702904.402864754
2225071.89933492702888.9315368142225078.93175671702823.108068849
#Sta/Elev= 30
       0 1835.15     1.2  1835.3    30.3 1831.49      39  1830.8    47.4 1830.73
      59 1831.18    72.3 1830.84    76.4 1830.01    80.4 1828.47    86.91826.713
    88.6 1826.17    92.6 1825.57    96.7  1825.6   101.31826.672   104.8 1827.77
   108.8 1828.25   127.9 1827.79   137.4 1827.09   144.3 1827.24   152.6 1826.88
   167.7 1827.87   171.5 1829.23   179.5 1833.56   183.5 1835.22   199.6  1836.9
   207.7 1838.37   215.7 1844.18   223.8  1846.7   227.8 1848.79   233.9  1853.2
#Mann= 4 ,-1,0
       0     .06       0    86.9    .045       0   101.3      .1       0
  118.91     .06       0
Bank Sta=86.9,101.3
XS Rating Curve= 0 ,0
Exp/Cntr(USF)=0,0
Exp/Cntr=0.3,0.1

Type RM Length L Ch R = 1 ,391     ,91.7,97.6,98
XS GIS Cut Line= 3
2225115.50035002703013.5460509522225078.65045984702876.835771333
2225082.86991291702830.703084383
#Sta/Elev= 30
       0 1830.63      17  1829.8    21.1 1829.83    29.4 1830.22    54.2 1830.41
    62.5 1831.04    66.7 1830.98    70.8 1829.92    74.9 1826.51    79.1 1824.06
    83.2 1823.64    87.4 1823.58    95.7 1823.75   97.06 1824.06   103.9 1825.63
   107.4 1826.09   112.2  1826.4   124.7 1826.52   128.8 1826.84   132.9 1828.13
   137.1 1830.15   145.3 1835.41   149.3 1836.47   157.2 1837.04   169.4 1838.59
   173.4 1841.29   177.4 1844.25   181.4 1845.45   185.4 1846.96   187.9 1848.28
#Mann= 3 ,-1,0
       0     .06       0    79.1    .045       0   97.06     .06       0
Bank Sta=79.1,97.06
XS Rating Curve= 0 ,0
Exp/Cntr(USF)=0,0
Exp/Cntr=0.3,0.1

Type RM Length L Ch R = 1 ,293     ,193.1,193.1,193.1
XS GIS Cut Line= 2
2225162.64603742703131.5327230882225182.56522664702813.731113269
#Sta/Elev= 30
       0  1839.3    22.4 1838.41    42.4 1838.26    70.5 1836.59   105.5 1831.31
   118.6  1830.3   138.6 1829.45   150.6 1829.94   174.7 1829.88   190.7 1830.66
   194.7 1829.77   198.7 1828.13   206.1 1826.53   222.8 1826.01  226.87 1823.84
   230.8 1822.43   234.8  1822.7  239.58 1823.84   242.8 1825.56   250.8 1832.09
   262.9 1840.35   266.9 1841.16   274.9 1841.29   278.9 1842.71   282.9 1845.22
   294.9 1847.15   298.9 1848.41   304.5 1851.06     315 1858.56   318.4 1859.81
#Mann= 5 ,-1,0
       0     .06       0     120      .1       0  226.87    .045       0
  239.58      .1       0  318.43     .06       0
Bank Sta=226.87,239.58
XS Rating Curve= 0 ,0
Exp/Cntr(USF)=0,0
Exp/Cntr=0.3,0.1

Type RM Length L Ch R = 1 ,100     ,,,
XS GIS Cut Line= 4
2225195.24107432703092.5997623412225300.26952657703033.747612374
2225397.14921959702894.3132878382225369.08127115702777.514405597
#Sta/Elev= 30
       0 1839.47    23.8 1836.69    46.9 1832.62    56.1 1831.63    74.4 1830.63
    92.8  1827.4    97.4 1827.02   121.1 1826.72   149.5 1827.58   163.8 1827.45
   203.9 1825.81  212.941823.883   218.5 1822.49   225.4 1822.67   232.4 1823.92
   234.8 1825.66   241.4 1831.57   244.3 1832.93   247.2 1833.58   295.5 1834.38
   299.6 1834.78   307.8 1837.44   311.9 1837.97   344.8 1838.62   365.4 1840.48
     386 1846.12   390.1    1849   398.3 1855.86   402.4 1857.79   410.3 1858.37
#Mann= 5 ,-1,0
       0     .06       0      50      .1       0  212.94    .045       0
   232.4      .1       0  270.39     .06       0
#XS Ineff= 2 , 0
          150.17 1830.74
Permanent Ineff=
       F       F
Bank Sta=212.94,232.4
XS Rating Curve= 0 ,0
Exp/Cntr(USF)=0,0
Exp/Cntr=0.3,0.1
LCMann Table=0

Chan Stop Cuts=-1
Use User Specified Reach Order=0
Composite Channel Slope=5